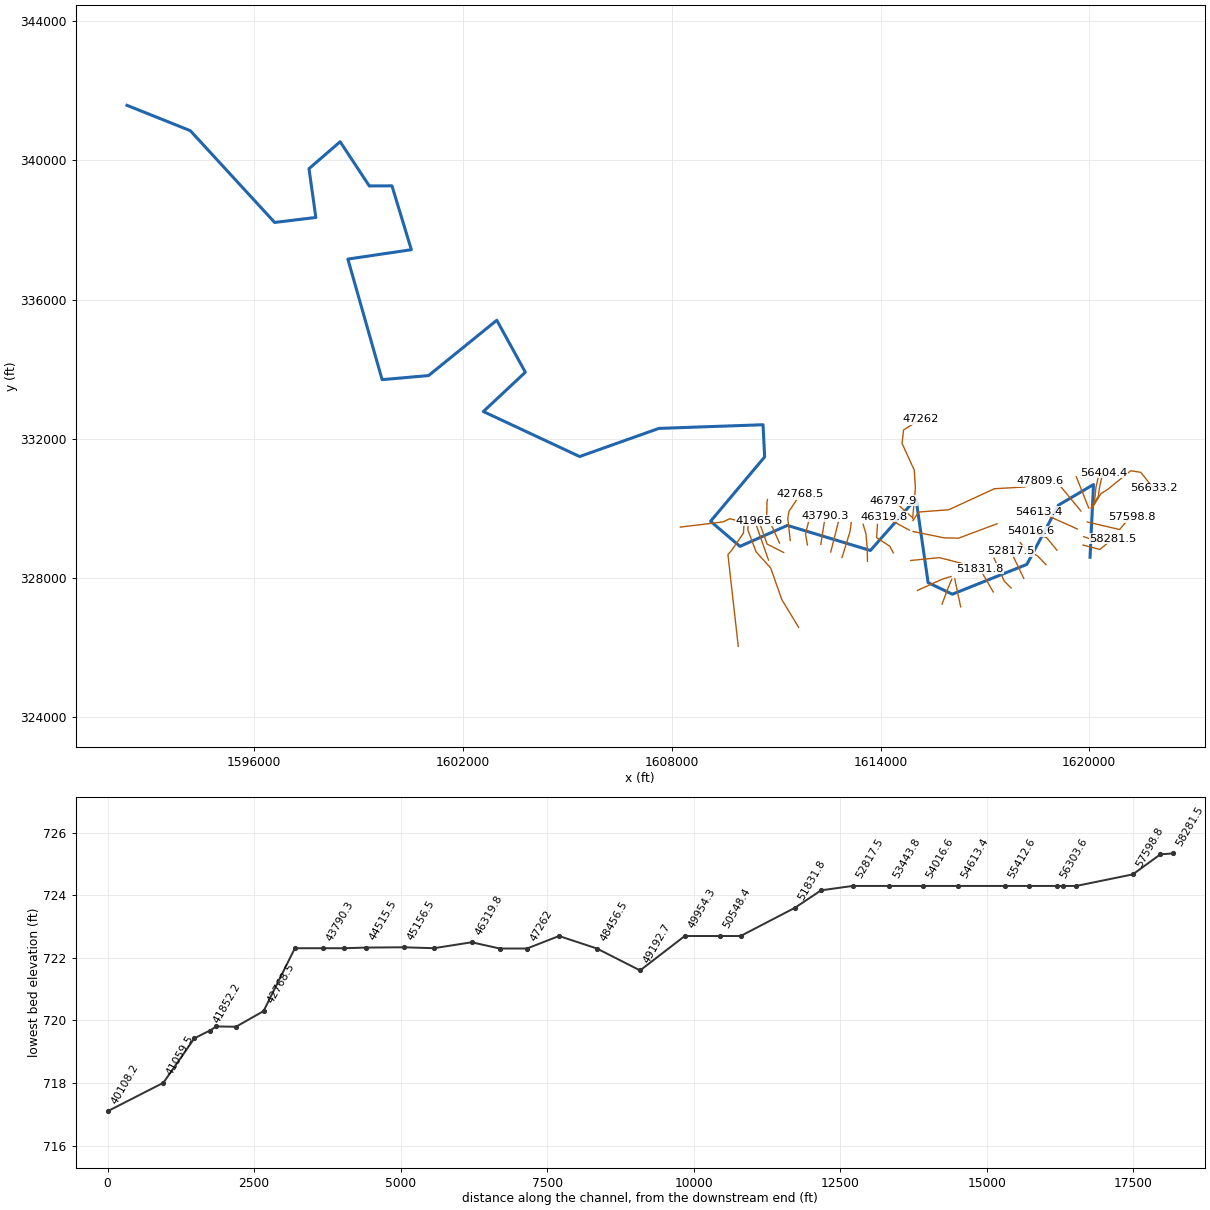
--- MCLRYCRK.prj (project) ---

Proj Title=MCLRYCRK
Current Plan=p01
Default Exp/Contr=0,0
English Units
Geom File=g01
Flow File=f01
Plan File=p01
BEGIN DESCRIPTION:
END DESCRIPTION:
DSS Export Rating Curves= 0
DSS Export Rating Curve Sorted= 0
DSS Export Volume Flow Curves= 0
DXF OffsetX= 0
DXF OffsetY= 0
DXF ScaleX= 0
DXF ScaleY= 0

--- MCLRYCRK.p01 (plan) ---

Plan Title=Floodplain
Program Version=4.00
Geom File=g01
Flow File=f01
K Sum by GR=0
Std Step Tol=0.01
Critical Tol=0.01
Num of Std Step Trials=20
Max Error Tol=0.3
Flow Tol Ratio=0.001
Split Flow NTrial=30
Split Flow Tol=0.02
Split Flow Ratio=0.02
Log Output Level=0
Friction Slope Method=1
Unsteady Friction Slope Method=2
Unsteady Bridges Friction Slope Method=1
Global Log Level=0
CheckData=False
Run HTab=0
Run UNet=0
Run PostProcess=0
UNET Theta=0
UNET Theta Warmup=0
UNET ZTol=0
UNET ZSATol=0
UNET MxIter=0
UNET MaxInSteps=0
UNET DtIC=0
UNET DtMin=0
UNET MaxCRTS=0
UNET WFStab=0
UNET SFStab=0
UNET WFX=0
UNET SFX=0
UNET DSS MLevel=0
UNET DZMax Abort=0
UNET Convert EG Bridges=0
UNET Use Existing IB Tables=0
UNET Froude Limit=0
UNET Froude Power=0
Write IC File=0
Echo Input=False
Echo Output=False
Write Detailed=0

--- MCLRYCRK.f01 (steady flow) ---

Flow Title=NFF Regression Equation
Program Version=4.10
Number of Profiles= 1
Profile Names=P100yr
River Rch & RM=MCLRYCRK,Main            ,58281.5
11443.23
River Rch & RM=MCLRYCRK,Main            ,47262
11821.34
River Rch & RM=MCLRYCRK,Main            ,41059.5
12226.13
River Rch & RM=MCLRYCRK,Main            ,32020.6
12341.37
River Rch & RM=MCLRYCRK,Main            ,24997.3
12597.38
River Rch & RM=MCLRYCRK,Main            ,20269.3
12737.29
River Rch & RM=MCLRYCRK,Main            ,11067.4
12828.44
Boundary for River Rch & Prof#=MCLRYCRK,Main            , 1
Up Type= 0
Dn Type= 3
Dn Slope=0.00025
DSS Import GetInterval= 0
DSS Import GetPeak= 0
DSS Import FillOption= 0

--- MCLRYCRK.g01 (geometry) ---

Geom Title=USGS 10m DEM
Program Version=4.10

River Reach=MCLRYCRK        ,Main
Reach XY= 30
     1620022.256      328602.391     1620122.175       330690.63
      1619115.04      330098.233     1618205.817      328396.256
     1616064.564      327539.947     1615367.275       327871.95
     1615018.317      330283.408     1613708.783      328795.936
     1611322.136      329516.047     1609959.289      328913.616
     1609113.803      329634.103     1610668.686      331483.253
       1610622.7      332407.259     1607628.737      332301.969
     1605350.404      331494.192     1602582.553      332786.881
     1603789.738      333915.641     1602968.905      335408.697
     1601008.488      333819.808     1599672.377      333702.447
     1598688.456      337164.947     1600512.655      337435.086
      1599955.71      339269.113     1599304.322      339265.641
     1598466.252      340535.218     1597570.988      339762.169
     1597767.074      338360.645      1596583.51      338217.191
     1594158.942      340852.853     1592338.799      341580.934

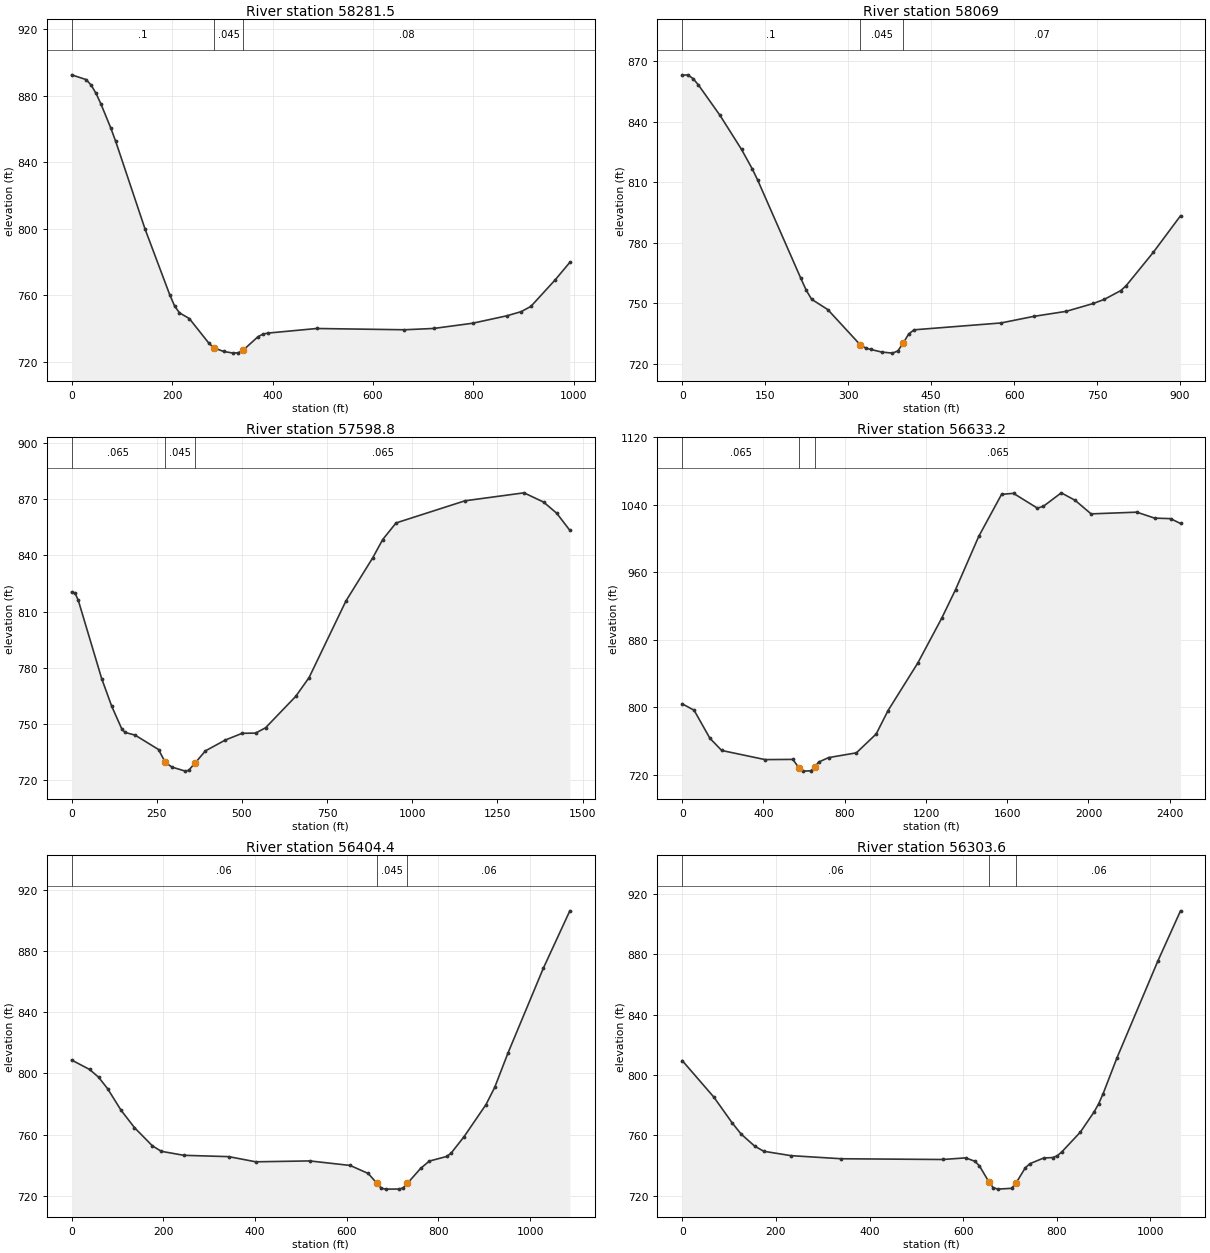
Type RM Length L Ch R = 1 ,58281.5 ,214.1,212.4,210.5
XS GIS Cut Line= 3
     1619820.477      328951.735     1620302.248      328825.867
     1620686.363      329136.197
#Sta/Elev= 30
       0  892.45    29.3  889.56      39  886.25    48.8  881.25    58.6  874.83
    78.1  860.48    87.9  852.43   146.4  799.73   195.3  760.47     205  753.69
   214.8  749.53   234.3  746.12   273.4  731.27   283.1  728.55   302.7  726.33
   322.2  725.34     332  725.58   341.7  727.18     371  735.17   380.8  736.75
   390.5  737.37   488.2  740.13   662.6  739.37   720.6  740.15   798.1  743.28
   865.9  747.72   894.9  750.24   914.3   753.4   962.7  769.35   991.8  779.85
#Mann= 3 , 0 , 0
       0      .1       0   283.1    .045       0   341.7     .08       0
Bank Sta=283.1,341.7
XS Rating Curve= 0 ,0
Exp/Cntr=0.3,0.1

Type RM Length L Ch R = 1 ,58069   ,467.9,470.2,472.6
XS GIS Cut Line= 3
     1619841.008      329193.094     1620264.825      329046.923
     1620702.236      329162.804
#Sta/Elev= 30
       0  862.98     9.8  863.22    19.5  861.36    29.2  858.23    68.2  843.15
   107.2  826.25   126.7  816.55   136.4  811.05   214.4  762.37   224.2  756.46
   233.9     752   263.1  746.89   321.6  729.49   331.4  727.85   341.1  727.11
   360.6  725.85   380.1  725.31   389.8   726.4   399.6  730.35   409.3  734.77
   419.1  736.86   576.2  740.26   635.2  743.51   694.2  746.02   743.4  749.93
   763.1  751.96   792.6  756.26   802.4  758.68   851.6  775.26   900.8  793.37
#Mann= 3 , 0 , 0
       0      .1       0   321.6    .045       0   399.6     .07       0
Bank Sta=321.6,399.6
XS Rating Curve= 0 ,0
Exp/Cntr=0.3,0.1

Type RM Length L Ch R = 1 ,57598.8 ,946.3,965.6,984.1
XS GIS Cut Line= 4
     1619943.964      329614.493     1620871.498      329397.268
     1621076.095      329640.712     1621228.895      329757.255
#Sta/Elev= 30
       0  820.44     9.8  819.99    19.6  816.06    88.4  774.14   117.8  759.39
   147.3  747.28   157.1  745.36   186.6  743.92   255.3  736.22     275  729.38
   294.6  726.84   333.9  724.67   343.7  725.12   363.4  729.17   392.8  735.49
   451.8  741.34   500.9   744.9   540.2     745   569.6  747.87     658  764.64
   697.3  774.71   805.3   815.6   883.9  838.67   913.4  848.51   952.6  857.39
    1155  869.23  1328.3  873.49  1385.9  868.53  1424.4  862.57  1462.8  853.43
#Mann= 3 , 0 , 0
       0    .065       0     275    .045       0   363.4    .065       0
Bank Sta=275,363.4
XS Rating Curve= 0 ,0
Exp/Cntr=0.3,0.1

Type RM Length L Ch R = 1 ,56633.2 ,212.3,228.8,246
XS GIS Cut Line= 6
     1620078.147      330007.936     1620330.075      330423.196
     1620543.616      330561.217     1621190.209      331085.088
     1621481.008      331041.686     1621845.591      330581.616
#Sta/Elev= 30
       0  804.03    58.3  796.46     136  763.28   194.3  748.77     408  737.96
   544.4   738.2   573.7  728.49   593.3   724.3   632.4  724.65     652  729.04
   671.5     735   720.4  740.33   857.2  745.96   954.8  768.29  1013.4  796.12
  1159.9   852.5  1277.1  905.32  1345.5  939.32  1459.8 1002.46  1572.2 1052.26
    1631 1053.44  1748.6  1035.9    1778 1038.07  1866.2 1054.05  1934.7 1045.11
  2012.9 1029.11    2238 1031.14    2326 1024.07  2404.3 1023.47  2453.2 1017.71
#Mann= 3 , 0 , 0
       0    .065       0   573.7    .045       0     652    .065       0
Bank Sta=573.7,652
XS Rating Curve= 0 ,0
Exp/Cntr=0.3,0.1

Type RM Length L Ch R = 1 ,56404.4 ,100.8,100.8,100.8
XS GIS Cut Line= 5
     1620066.429      330007.936     1620261.143      330359.272
     1620294.318      330602.258     1620354.565      330871.638
     1620405.595      331027.363
#Sta/Elev= 30
       0   808.8    39.2  802.63    58.8  797.59    78.4  790.12   107.8  775.98
   137.2  764.55   176.4   752.6   195.9  749.03   244.9  746.43   342.9  745.56
   401.7  742.18   519.4  742.76   607.7  739.79   646.9  734.56     666  728.18
   675.5  724.86     685   724.3   714.4  724.36   723.1  725.06   732.6  728.11
   761.2  737.82   780.2  742.64   818.3  745.68   827.8  747.83   856.3  758.72
   903.9  779.62     923  790.95   951.9  813.39    1029  868.86  1086.8  906.42
#Mann= 3 , 0 , 0
       0     .06       0     666    .045       0   732.6     .06       0
Bank Sta=666,732.6
XS Rating Curve= 0 ,0
Exp/Cntr=0.3,0.1

Type RM Length L Ch R = 1 ,56303.6 ,455.9,469.4,483
XS GIS Cut Line= 5
     1620057.314      330020.088      1620157.14      330250.991
     1620193.655      330612.866     1620255.607      330889.867
     1620266.272      331054.706
#Sta/Elev= 30
       0  809.49    67.7  785.22   106.4  768.31   125.8  760.78   154.8  752.78
   174.2  749.39   232.2  746.49     340  744.43   556.3  743.94   605.4  745.01
   625.1  742.77   634.8  739.74   655.1729.0607   664.2   725.3     674   724.3
   703.4  724.84   713.2  728.44   732.7  738.41   742.5  741.15   771.9  744.91
   791.4  745.23   801.2  746.42     811  749.06   850.2  762.02   879.5  775.37
   889.3  780.75   899.1  787.65   928.3  811.11  1015.7  875.33  1064.3  908.75
#Mann= 3 , 0 , 0
       0     .06       0   655.1    .045       0   713.2     .06       0
Bank Sta=655.1,713.2
XS Rating Curve= 0 ,0
Exp/Cntr=0.3,0.1

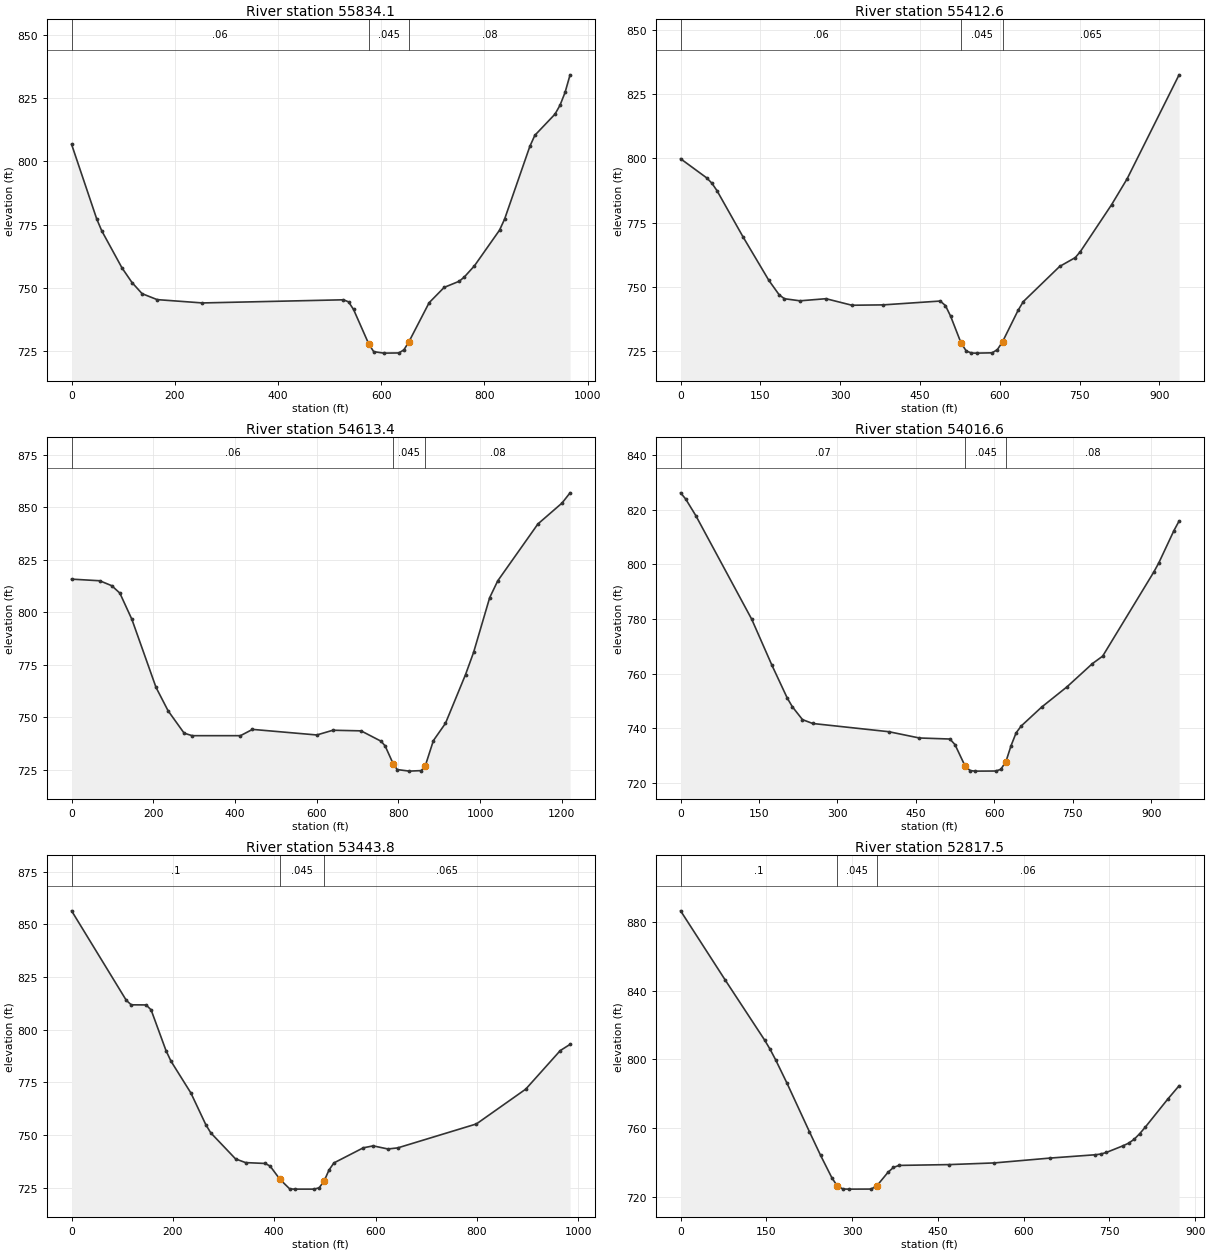
Type RM Length L Ch R = 1 ,55834.1 ,414.4,421.5,428.5
XS GIS Cut Line= 2
     1619985.561      330014.314     1619627.314      330911.235
#Sta/Elev= 30
       0  806.75    48.8  777.23    58.5  772.57    97.6  757.98   117.1  752.17
   136.6  747.78   165.8  745.43   253.6  744.12   526.8  745.36   536.6  744.55
   546.3  741.54   575.6     728   585.3  724.88   604.9   724.3   634.1  724.37
   643.9  725.61   653.6   728.8   692.7   744.2   721.9  750.26   751.2   752.7
     761  754.38   780.5  758.77   829.2  772.88     839  777.25   887.8  805.91
   897.5   810.3   936.6  818.68   946.3  822.18   956.1  827.24   965.8   834.2
#Mann= 3 , 0 , 0
       0     .06       0   575.6    .045       0   653.6     .08       0
Bank Sta=575.6,653.6
XS Rating Curve= 0 ,0
Exp/Cntr=0.3,0.1

Type RM Length L Ch R = 1 ,55412.6 ,788.9,799.2,809.4
XS GIS Cut Line= 2
     1619762.527      329927.867     1619164.312      330648.838
#Sta/Elev= 30
       0   799.8    48.8  792.41    58.6  790.36    68.3  787.44   117.1  769.54
   165.9  752.55   185.4  746.91   195.2  745.43   224.4  744.62   273.2  745.44
     322   742.9   380.6  743.04   487.9  744.53   497.7  742.78   507.4  738.68
     527  728.27   536.7  725.18   546.5  724.32   556.2   724.3   585.5  724.42
   595.3  725.66     605   728.7   634.3  740.94   644.1  744.32   712.4  757.98
   741.7   761.4   751.4  763.77     810  781.97   839.2  792.02   936.8   832.4
#Mann= 3 , 0 , 0
       0     .06       0     527    .045       0     605    .065       0
Bank Sta=527,605
XS Rating Curve= 0 ,0
Exp/Cntr=0.3,0.1

Type RM Length L Ch R = 1 ,54613.4 ,596.2,596.8,597.4
XS GIS Cut Line= 2
      1619655.68        329413.7      1618542.56      329913.351
#Sta/Elev= 30
       0  815.83    68.9  815.06    98.4  812.69   118.1  809.17   147.6  796.66
   206.6  764.25   236.2  753.07   275.5  742.39   295.2   741.2   413.3   741.2
   442.8   744.2   600.2  741.54   639.6  743.79   708.5   743.5   757.6  738.55
   767.5   736.3   787.2  727.77     797  725.05   826.5   724.3     856  724.55
   865.9  726.95   885.6  738.87   915.1  747.08   964.3  770.36     984  780.94
  1023.3  806.97    1043     815  1141.4  842.14  1200.4   852.1  1220.1  856.98
#Mann= 3 , 0 , 0
       0     .06       0   787.2    .045       0   865.9     .08       0
Bank Sta=787.2,865.9
XS Rating Curve= 0 ,0
Exp/Cntr=0.3,0.1

Type RM Length L Ch R = 1 ,54016.6 ,575,572.8,570.4
XS GIS Cut Line= 3
     1619071.393      328804.228     1618781.142      329156.603
     1618322.834      329347.962
#Sta/Elev= 30
       0  826.24     9.7  823.98    29.1  817.89     136  779.94   174.8  763.02
     204  751.05   213.7  747.88   233.1  743.16   252.6  741.75   398.2  738.74
   456.5  736.44     515  736.06   524.7  734.01   544.2  726.09   553.9  724.49
   563.6   724.3   602.6  724.34   612.3  724.95   622.1  727.79   631.8  733.57
   641.6  738.33   651.3  740.82   690.2  747.72   738.9  755.18   787.6   763.7
   807.1  766.42   904.5  797.11   914.2  800.49   943.4  812.42   953.2   815.9
#Mann= 3 , 0 , 0
       0     .07       0   544.2    .045       0   622.1     .08       0
Bank Sta=544.2,622.1
XS Rating Curve= 0 ,0
Exp/Cntr=0.3,0.1

Type RM Length L Ch R = 1 ,53443.8 ,640.4,626.3,612.2
XS GIS Cut Line= 4
     1618753.793      328389.731     1618516.094      328637.659
     1618175.761      328823.211     1618017.682      329020.808
#Sta/Elev= 30
       0  856.47     108  813.96   117.8  811.83   147.2  811.78     157  809.42
   186.4  790.09   196.3  785.04   235.5  769.97     265  754.91   274.8  751.02
   323.8  738.64   343.5   736.9   382.2  736.49   391.9  735.25   411.3  728.98
   430.7  724.39   440.4   724.3   479.1   724.3   488.8  724.96   498.5  728.11
   508.2  733.38   517.9  736.75     576  743.93   595.4  744.84   624.5  743.37
   643.9  743.89   799.2  755.26   896.6  771.79   964.7  790.09   984.1  793.05
#Mann= 3 , 0 , 0
       0      .1       0   411.3    .045       0   498.5    .065       0
Bank Sta=411.3,498.5
XS Rating Curve= 0 ,0
Exp/Cntr=0.3,0.1

Type RM Length L Ch R = 1 ,52817.5 ,537.6,537,536.4
XS GIS Cut Line= 2
     1618116.268      327995.502     1617741.098      328782.526
#Sta/Elev= 30
       0  886.59    78.4  846.06   146.9  811.26   156.7  805.77   166.5  799.53
   186.1  786.08   225.3  757.81   244.9  743.97   264.5  730.98   274.3  726.03
   284.1  724.38   293.9   724.3   333.1  724.34   342.9  726.08   362.5  734.01
   372.3  736.97   382.1  738.13   470.2  738.61   548.6  739.58   646.6  742.42
   724.9  744.33   734.7  744.74   744.5  745.66   773.9  749.58   783.7   751.1
   793.5  753.41   803.3  756.73   813.1  760.57   852.3  776.87   871.9  784.58
#Mann= 3 , 0 , 0
       0      .1       0   274.3    .045       0   342.9     .06       0
Bank Sta=274.3,342.9
XS Rating Curve= 0 ,0
Exp/Cntr=0.3,0.1

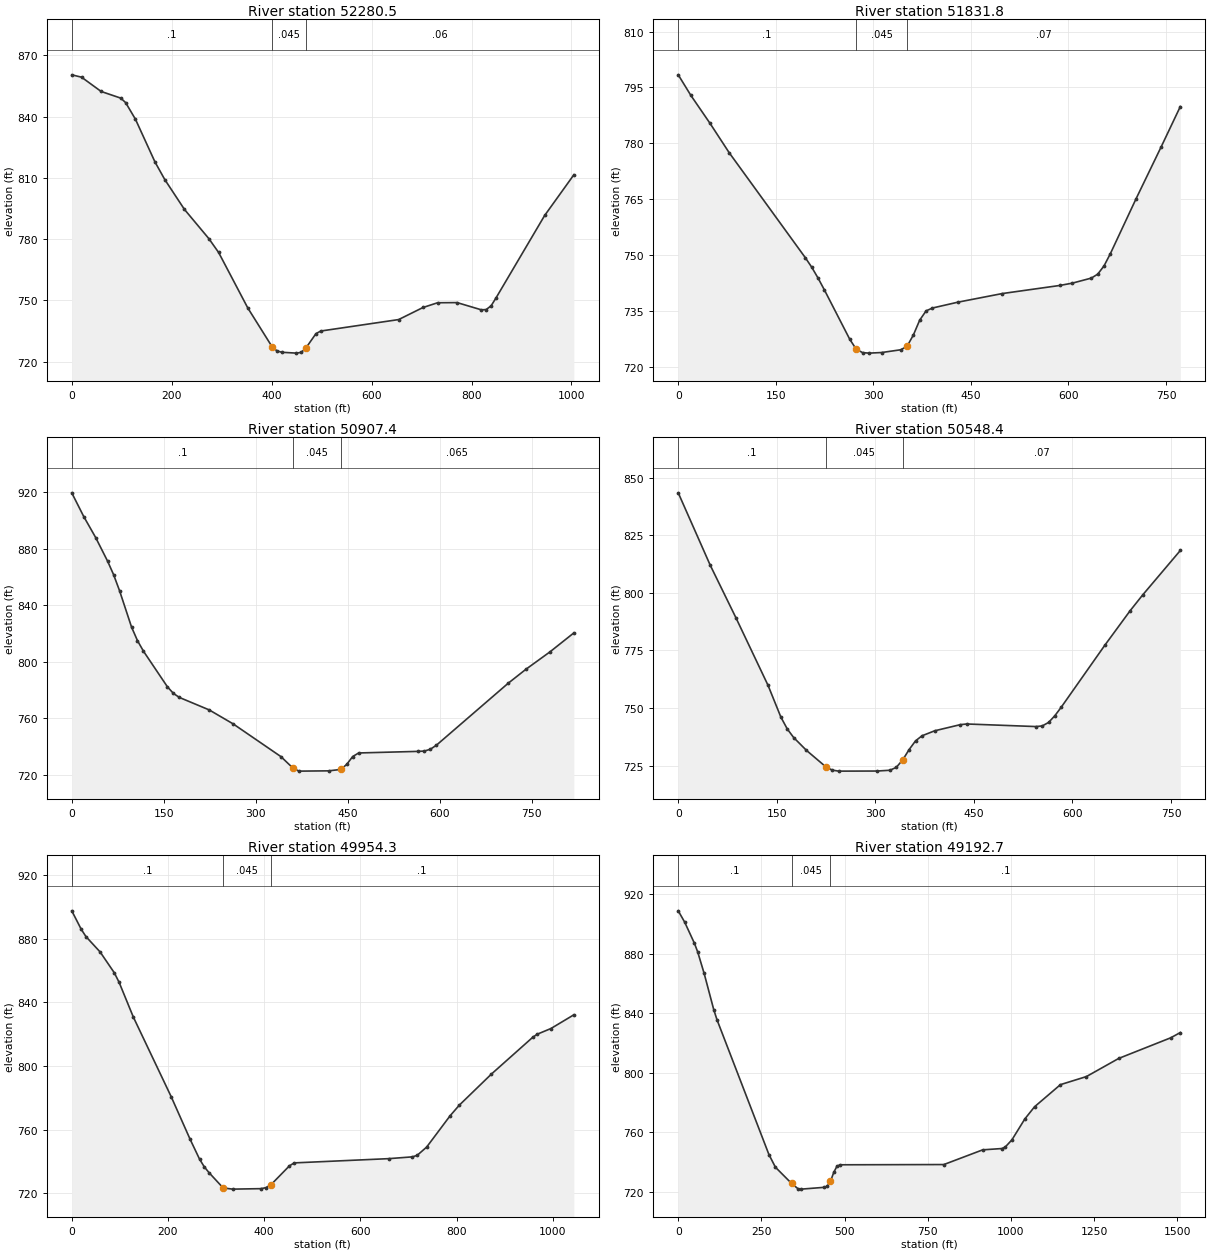
Type RM Length L Ch R = 1 ,52280.5 ,446.3,448.7,451.1
XS GIS Cut Line= 3
     1617754.344      327719.056     1617558.066      327910.807
     1617261.722      328578.431
#Sta/Elev= 30
       0  860.41    19.6  859.25    58.8  852.26      98  849.01   107.8  846.81
   127.4  838.69   166.6  817.71   186.2  809.11   225.4  794.55   274.4   780.2
   293.9  773.44   352.3  746.26     401  727.24   410.7  725.26   420.5  724.58
   449.7  724.16   459.4  724.55   469.2  726.89   488.7   733.7   498.4  734.98
   654.2  740.59   702.9   746.5   732.1  748.82   771.1   748.9   819.8  745.35
   829.5   745.5   839.3  747.36     849  751.17   946.4  791.56  1004.8  811.46
#Mann= 3 , 0 , 0
       0      .1       0     401    .045       0   469.2     .06       0
Bank Sta=401,469.2
XS Rating Curve= 0 ,0
Exp/Cntr=0.3,0.1

Type RM Length L Ch R = 1 ,51831.8 ,931.5,924.4,917.3
XS GIS Cut Line= 2
     1617239.097      327604.621     1616852.812      328273.024
#Sta/Elev= 30
       0  798.37    19.5  792.82    48.9  785.33    78.2  777.48   195.4  749.24
   205.2   746.7     215  743.76   224.8  740.56   263.8   727.3   273.6  724.68
   283.4  723.74   293.2   723.6   312.7  723.76     342   724.5   351.8  725.41
   361.6  728.49   371.3  732.47   381.1  734.95   390.9  735.72     430  737.29
   498.4  739.61   586.3  741.77   605.9   742.4   635.2  743.76     645  744.82
   654.7  747.03   664.5  750.34   703.6  764.94   742.7  779.07     772  789.85
#Mann= 3 , 0 , 0
       0      .1       0   273.6    .045       0   351.8     .07       0
Bank Sta=273.6,351.8
XS Rating Curve= 0 ,0
Exp/Cntr=0.3,0.1

Type RM Length L Ch R = 1 ,50907.4 ,371.8,359,345.9
XS GIS Cut Line= 3
     1616303.695       327177.92     1616218.812      327578.526
     1616133.928      327979.132
#Sta/Elev= 30
       0   919.6    19.5  902.84      39  887.95    58.5  871.19    68.2  861.72
      78  850.29    97.5  824.63   107.2     815     117  807.52     156  782.37
   165.8  777.69   175.5  774.84   224.2  766.01   263.2  756.14   341.2  732.96
   360.8  724.85   370.5   722.7   419.2   722.9   438.8   723.9   448.5  727.46
   458.2     733     468  735.55   565.5  736.68   575.2   736.9     585   738.2
   594.8  741.04   711.8  784.84     741  794.82     780  807.06     819  820.49
#Mann= 3 , 0 , 0
       0      .1       0   360.8    .045       0   438.8    .065       0
Bank Sta=360.8,438.8
XS Rating Curve= 0 ,0
Exp/Cntr=0.3,0.1

Type RM Length L Ch R = 1 ,50548.4 ,611.9,594.2,576.6
XS GIS Cut Line= 3
     1615767.743      327253.058     1615923.993      327674.065
     1616045.521      327964.864
#Sta/Elev= 30
       0  843.36    48.8  811.91    87.9  789.14   136.7  759.89   156.2  746.14
     166  740.96   175.7  737.26   195.2  731.69   224.5   724.6   234.3  723.15
   244.1   722.7   302.6  722.74   322.2  723.08   331.9  724.33   341.7  727.59
   351.4  732.04   361.2  735.82     371  738.02   390.5   740.2   429.5  742.86
   439.3  743.14   544.6  742.02   554.1   742.3   563.7  743.81   573.2  746.71
   582.8  750.35   649.6   777.4   687.8  792.24   706.9  799.08   764.2  818.36
#Mann= 3 , 0 , 0
       0      .1       0   224.5    .045       0   341.7     .07       0
Bank Sta=224.5,341.7
XS Rating Curve= 0 ,0
Exp/Cntr=0.3,0.1

Type RM Length L Ch R = 1 ,49954.3 ,768.9,761.6,754.2
XS GIS Cut Line= 3
     1615063.888       327649.94     1615771.453      327971.054
     1616026.219      328049.366
#Sta/Elev= 30
       0  897.45    19.7  885.84    29.5  881.27      59   871.6    88.5   858.5
    98.4  852.56   127.9  830.79   206.6  780.77   245.9  754.06   265.6  741.53
   275.4  736.72   285.2  733.08   314.7  723.44   334.4   722.7   393.4     723
   403.3   723.6   413.1  725.18   452.4  737.31   462.3  739.17     659  741.84
   708.2  742.97     718  743.93   737.7  749.12   786.5   768.8   805.6  775.45
   872.2  794.93   957.9  817.98   967.4  819.96     996  823.55  1043.6  832.16
#Mann= 3 , 0 , 0
       0      .1       0   314.7    .045       0   413.1      .1       0
Bank Sta=314.7,413.1
XS Rating Curve= 0 ,0
Exp/Cntr=0.3,0.1

Type RM Length L Ch R = 1 ,49192.7 ,742.9,736.2,729.4
XS GIS Cut Line= 3
     1614868.045      328508.914     1615691.585      328590.737
     1616351.771       328421.03
#Sta/Elev= 30
       0   908.9    19.5  901.22    48.7  887.04    58.4  881.29    77.9  866.77
   107.1   842.1   116.8  835.42   272.6  744.88   292.1  736.35   340.8  725.42
   360.2  721.83     370   721.6   438.1   722.8   447.9   723.5   457.6  726.82
   467.4   732.8   477.1  737.04   486.8  737.98   798.4  738.14   915.2  748.04
   973.7  748.93   983.4  750.05  1002.9  754.72  1041.8  768.82    1071  777.02
  1148.9  791.92  1226.8  797.34  1324.2  809.58    1480  823.41  1509.2  826.97
#Mann= 3 , 0 , 0
       0      .1       0   340.8    .045       0   457.6      .1       0
Bank Sta=340.8,457.6
XS Rating Curve= 0 ,0
Exp/Cntr=0.3,0.1

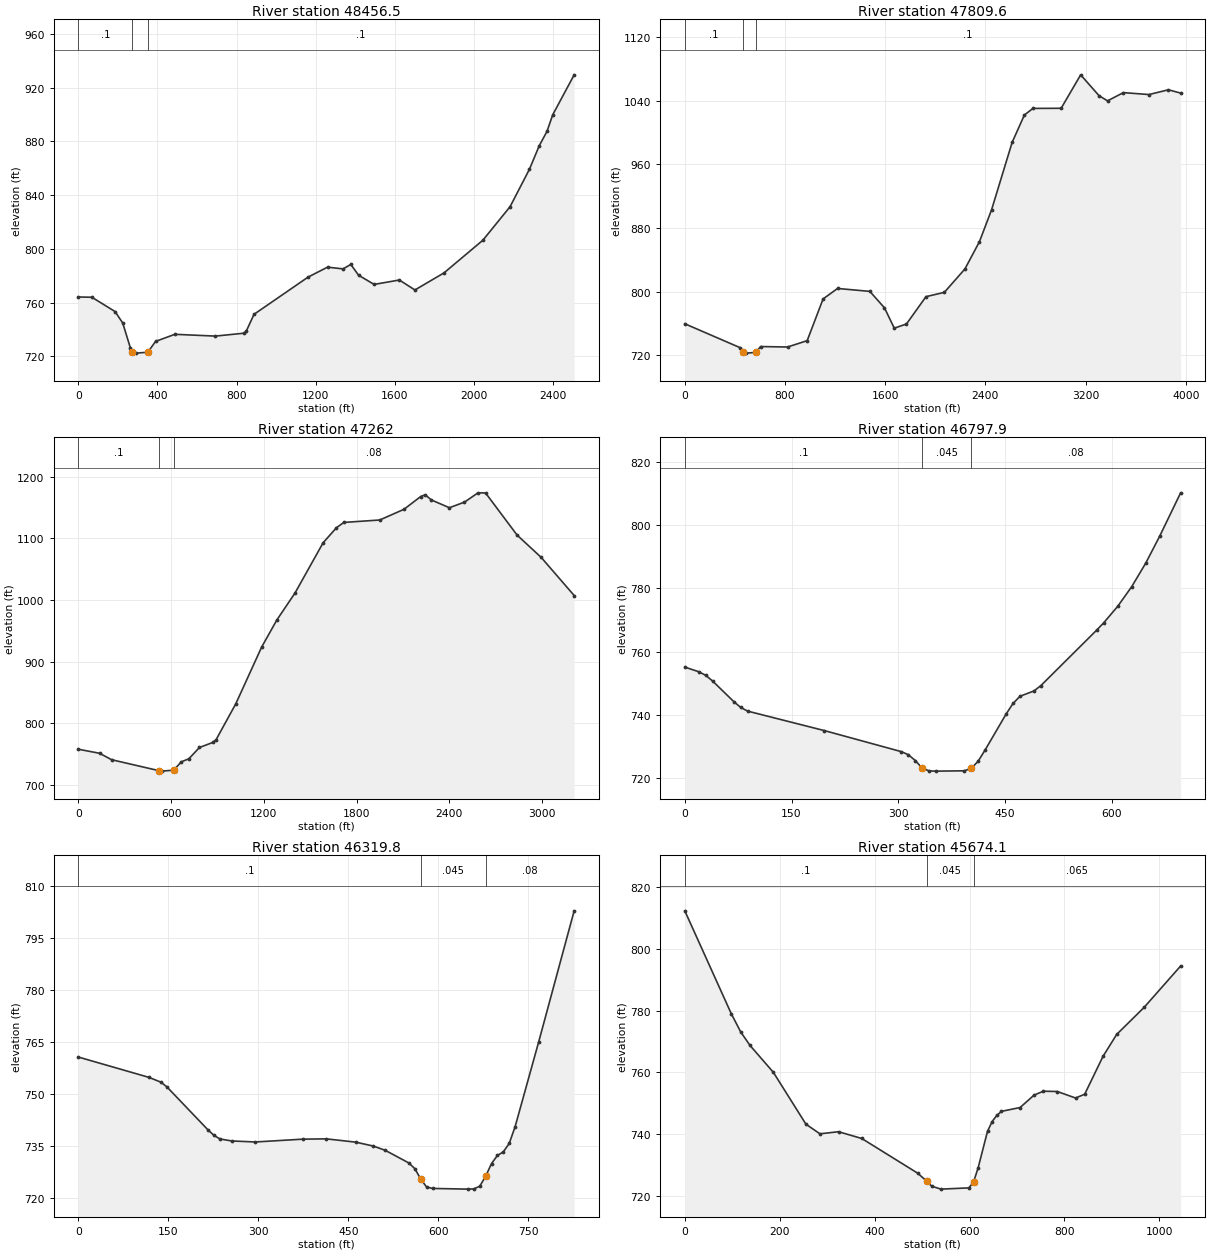
Type RM Length L Ch R = 1 ,48456.5 ,640.7,646.9,653.1
XS GIS Cut Line= 4
     1614935.591      329340.946     1615824.656      329159.662
     1616245.081      329150.019     1617348.216       329562.73
#Sta/Elev= 30
       0  764.13    68.3  763.94   185.4   753.3   224.4  744.75   263.4  725.99
   273.2  722.96   292.7   722.3   351.2  722.97   390.3  731.03   487.8  736.32
   692.7  734.99   839.1  737.18   848.8   738.7   887.8  751.21  1161.6     779
  1259.4  786.36  1337.7  785.07    1377  788.38  1416.2  780.35  1494.8  773.49
  1622.4  776.78  1700.9  769.35  1848.1   782.1  2044.4  806.43  2181.8   831.4
    2280  859.39    2329  876.75  2368.3   887.5  2397.7  899.97  2505.7  929.66
#Mann= 3 , 0 , 0
       0      .1       0   273.2    .045       0   351.2      .1       0
Bank Sta=273.2,351.2
XS Rating Curve= 0 ,0
Exp/Cntr=0.3,0.1

Type RM Length L Ch R = 1 ,47809.6 ,515.5,547.5,579.1
XS GIS Cut Line= 6
     1614933.662      329655.301     1615093.732      329900.228
     1615961.583      329965.799     1617273.389      330569.518
     1618138.852      330619.669      1618577.22      330780.259
#Sta/Elev= 30
       0   759.6   439.3   729.7   468.6   724.3   488.2   722.7   566.4  723.53
   605.5  730.96   820.7   730.4   977.1  738.36  1104.2  790.78  1219.8  803.95
  1477.6  800.26  1594.5  779.53  1672.5  754.05  1769.9   759.3  1925.8  793.66
    2072  799.02  2236.6  828.44  2352.6  862.73  2449.3  902.71  2613.7   987.5
  2711.4 1021.88  2779.9 1030.15  3004.9 1030.31  3160.8 1072.35  3306.9 1046.24
  3375.1 1039.62  3501.8    1050    3706 1047.57  3861.6 1053.55  3958.9  1049.4
#Mann= 3 , 0 , 0
       0      .1       0   468.6    .045       0   566.4      .1       0
Bank Sta=468.6,566.4
XS Rating Curve= 0 ,0
Exp/Cntr=0.3,0.1

Type RM Length L Ch R = 1 ,47262   ,442.9,464.1,485.1
XS GIS Cut Line= 6
     1614922.091      329711.229      1615003.09      330588.723
     1614968.376      331107.505     1614619.104      331868.584
     1614660.771      332256.605     1615144.061      332564.114
#Sta/Elev= 30
       0  757.82   137.1  751.26   215.4  740.81   518.9  723.18   538.5   722.3
   616.9  723.86   665.8  737.36   714.8  742.31   783.3  760.64   871.4     769
     891  773.34  1018.6  831.65  1185.3  923.43  1283.4  967.32  1401.2  1011.2
  1583.1 1092.75  1669.2 1117.14  1717.1 1125.76  1949.3  1129.7  2105.9 1147.03
  2214.1 1167.75  2243.6 1170.66  2282.6 1162.29  2399.7  1149.6  2497.3 1158.69
  2585.1 1173.78  2633.9 1173.52  2837.8 1105.17  2993.1 1069.12  3206.7 1007.21
#Mann= 3 , 0 , 0
       0      .1       0   518.9    .045       0   616.9     .08       0
Bank Sta=518.9,616.9
XS Rating Curve= 0 ,0
Exp/Cntr=0.3,0.1

Type RM Length L Ch R = 1 ,46797.9 ,472.2,478.1,484
XS GIS Cut Line= 2
     1614891.266      329761.908     1614375.346      330230.535
#Sta/Elev= 30
       0  755.14    19.6  753.68    29.4  752.55    39.3   750.7    68.7  744.28
    78.5  742.42    88.4  741.24   196.3  735.09   304.3  728.46   314.1   727.5
     324  725.65   333.8  723.21   343.6  722.37   353.4   722.3   392.7   722.4
   402.5  723.13   412.3  725.41   422.1  728.95   451.6  740.29   461.4  743.67
   471.2  745.93   490.8  747.61   500.6  749.31   579.2  766.86     589  769.15
   608.6  774.34   628.3  780.56   647.9  787.94   667.5  796.44     697  810.16
#Mann= 3 , 0 , 0
       0      .1       0   333.8    .045       0   402.5     .08       0
Bank Sta=333.8,402.5
XS Rating Curve= 0 ,0
Exp/Cntr=0.3,0.1

Type RM Length L Ch R = 1 ,46319.8 ,648.2,645.7,643.3
XS GIS Cut Line= 2
     1614829.071      329381.082     1614099.904      329769.971
#Sta/Elev= 30
       0  760.57   118.1  754.69   137.7  753.32   147.6  751.97   216.4  739.52
   226.3  737.97   236.1  736.96   255.8  736.38   295.1  736.09   373.8   736.9
   413.2  736.99   462.4  736.04   491.9   734.9   511.6  733.68   550.9  730.04
   560.8  728.41   570.6  725.44   580.4  723.12   590.3   722.7   649.3   722.5
   659.1  722.56     669  723.33   678.8  726.18   688.7  729.88   698.5   732.2
   708.3  733.24   718.2  735.68     728   740.5   767.4  765.01   826.4  802.71
#Mann= 3 , 0 , 0
       0      .1       0   570.6    .045       0   678.8     .08       0
Bank Sta=570.6,678.8
XS Rating Curve= 0 ,0
Exp/Cntr=0.3,0.1

Type RM Length L Ch R = 1 ,45674.1 ,539.2,517.6,495.9
XS GIS Cut Line= 5
     1614367.152      328728.903     1614262.985      328918.139
     1613886.249      329166.403     1613894.929      329274.041
     1613910.554      329543.139
#Sta/Elev= 30
       0  812.23    98.2   778.9   117.8   773.1   137.5  768.72   186.6  760.05
   255.2   743.3   284.7  740.18   323.9  740.86   372.9  738.67   490.6  727.47
   510.3  724.81   520.1  723.26   539.7  722.31   598.5  722.71   608.3  724.55
   618.2  729.28   637.8  740.99   647.6  744.16   657.4  746.11   667.2  747.44
   706.5  748.68   735.9  752.69   755.6  753.95   784.8  753.85   823.3  751.75
   842.6  752.98   881.1  765.19     910   772.3   967.7  781.02  1044.7   794.4
#Mann= 3 , 0 , 0
       0      .1       0   510.3    .045       0   608.3    .065       0
Bank Sta=510.3,608.3
XS Rating Curve= 0 ,0
Exp/Cntr=0.3,0.1

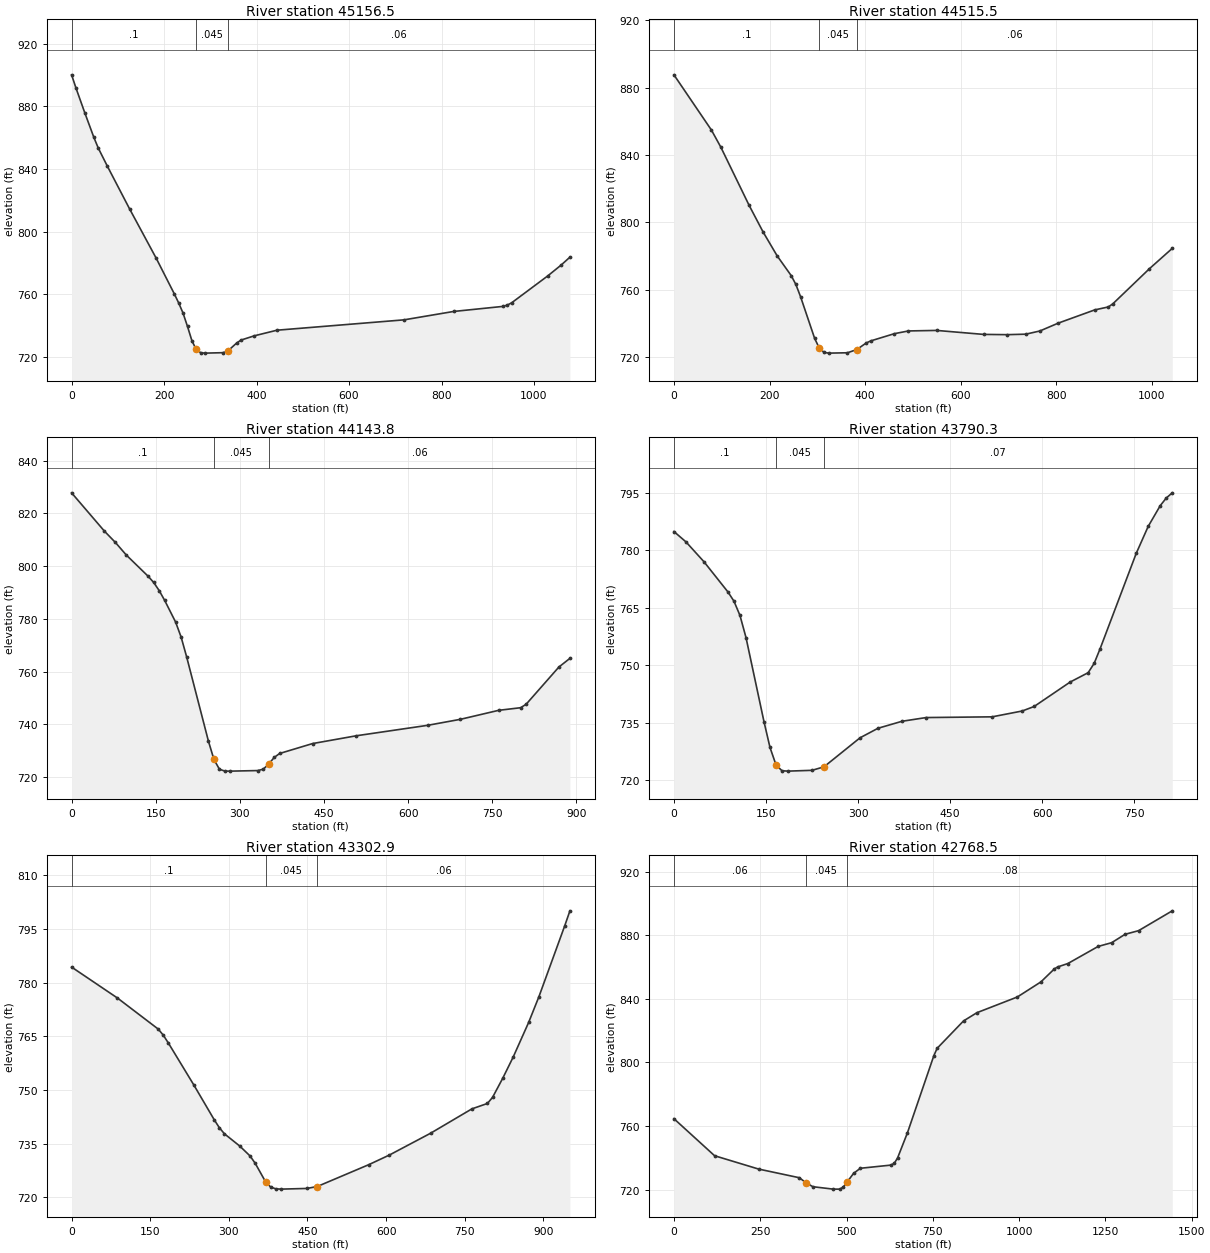
Type RM Length L Ch R = 1 ,45156.5 ,648.4,641.1,633.7
XS GIS Cut Line= 4
     1613625.526      328484.205     1613614.303      328888.975
     1613581.575      329270.198     1613499.096      329548.347
#Sta/Elev= 30
       0  900.06     9.6  891.54    28.9  875.54    48.2  860.09    57.8  853.23
    77.1  841.87   125.3  814.53   183.2  782.83   221.8   760.4   231.4  754.52
     241  747.94   250.7  739.35   260.3   730.2   269.4724.7306   279.6  722.54
   289.2  722.34   327.8  722.63   337.4  723.58   356.7  728.71   366.4  730.67
   395.3  733.41   444.2  736.98   718.9  743.59   826.2  748.95   932.6  752.17
   942.3  752.99     952  754.54  1029.3  771.55  1058.3  778.47  1077.7  783.62
#Mann= 3 , 0 , 0
       0      .1       0   269.4    .045       0   337.4     .06       0
Bank Sta=269.4,337.4
XS Rating Curve= 0 ,0
Exp/Cntr=0.3,0.1

Type RM Length L Ch R = 1 ,44515.5 ,370.5,371.7,372.8
XS GIS Cut Line= 3
     1612892.386      328592.376     1613121.347      329333.286
     1613157.082       329598.26
#Sta/Elev= 30
       0  887.56    78.5  854.75    98.2  844.58   157.1   810.2   186.5   794.3
     216  780.08   245.4  768.36   255.2  763.08     265  755.82   294.5  731.04
   304.3  725.26   314.1  722.79   323.9  722.33   363.2  722.54   382.8  724.48
   402.5  728.38   412.3  729.63   461.4  733.89   490.8   735.5   549.7  735.81
   647.9  733.45     697  733.29   736.2  733.58   765.7  735.47   804.1  740.13
   880.5  747.99   909.2  749.76   918.7  751.67   995.1  772.47  1042.8  784.52
#Mann= 3 , 0 , 0
       0      .1       0   304.3    .045       0   382.8     .06       0
Bank Sta=304.3,382.8
XS Rating Curve= 0 ,0
Exp/Cntr=0.3,0.1

Type RM Length L Ch R = 1 ,44143.8 ,351.2,353.5,355.7
XS GIS Cut Line= 2
     1612568.654       328752.61     1612787.404      329613.721
#Sta/Elev= 30
       0  827.77    58.6  813.24    78.1  808.97    97.6  804.19   136.7  796.11
   146.4  793.79   156.2  790.72     166     787   185.5  778.78   195.3  773.11
     205  765.72   244.1  733.58   253.8  726.73   263.6  723.02   273.4  722.32
   283.1  722.31     332  722.52   341.7  723.05   351.5  724.96   361.2  727.49
     371     729   429.6  732.75   507.7  735.71   634.6  739.66   693.2  741.94
   761.5  745.35   800.6  746.34   810.4  747.64   868.9  761.77   888.5  765.04
#Mann= 3 , 0 , 0
       0      .1       0   253.8    .045       0   351.5     .06       0
Bank Sta=253.8,351.5
XS Rating Curve= 0 ,0
Exp/Cntr=0.3,0.1

Type RM Length L Ch R = 1 ,43790.3 ,489.4,487.3,485.1
XS GIS Cut Line= 2
     1612283.932       328971.36     1612408.932      329773.443
#Sta/Elev= 30
       0  784.84    19.6  782.14    48.9  776.96      88  769.07    97.8  766.66
   107.6  762.93   117.4  757.17   146.7  735.22   156.5  728.48   166.3  723.93
     176  722.41   185.8  722.31     225  722.52   244.5  723.44   303.2  731.01
   332.5   733.5   371.6  735.32   410.8  736.29   518.4  736.48   567.3     738
   586.8  739.18   645.5  745.56   674.8     748   684.6  750.44   694.4  754.31
   753.1  779.14   772.6  786.18   792.2  791.59     802  793.58   811.8  794.94
#Mann= 3 , 0 , 0
       0      .1       0   166.3    .045       0   244.5     .07       0
Bank Sta=166.3,244.5
XS Rating Curve= 0 ,0
Exp/Cntr=0.3,0.1

Type RM Length L Ch R = 1 ,43302.9 ,526.6,534.4,542.7
XS GIS Cut Line= 3
     1611898.515      328953.999      1611842.96      329269.971
     1611995.738      329881.082
#Sta/Elev= 30
       0  784.37    87.5  775.72   165.3  767.04     175  765.33   184.7  763.13
   233.3   751.4   272.2  741.68   281.9  739.48   291.6  737.77   320.8  734.35
   340.5  731.58   350.4  729.51     370  724.38   379.9  722.88   389.7  722.39
   399.6  722.31   448.8   722.5   468.5  723.03   566.9  729.14   606.2  731.83
     685  737.94   763.7  744.74   793.3  746.25   803.1  747.95   822.8  753.37
   842.5  759.23     872  768.91   891.7  776.14   940.9  795.94   950.7  800.09
#Mann= 3 , 0 , 0
       0      .1       0     370    .045       0   468.5     .06       0
Bank Sta=370,468.5
XS Rating Curve= 0 ,0
Exp/Cntr=0.3,0.1

Type RM Length L Ch R = 1 ,42768.5 ,463.4,470.5,476.9
XS GIS Cut Line= 4
     1611404.592      329084.207     1611332.876      329718.375
     1611370.738      329925.353     1611701.467      330420.145
#Sta/Elev= 30
       0   764.6   117.8   741.3   245.5  732.91   363.3  727.47   382.9  724.28
   402.6  721.82   461.5   720.3   481.1   720.3   490.9  721.69   500.8  724.48
   520.4  730.19     540  733.41   628.4   735.4   638.2   736.5   647.8  739.81
   676.5  755.69     753  804.18   762.5  808.84   839.1  826.09   877.9  831.26
     995  841.14  1063.3  850.63  1102.3  858.82    1112  860.05  1141.3  862.17
  1229.1  872.93  1268.2  875.28  1307.2  880.57  1346.2  882.84  1443.8  895.32
#Mann= 3 , 0 , 0
       0     .06       0   382.9    .045       0   500.8     .08       0
Bank Sta=382.9,500.8
XS Rating Curve= 0 ,0
Exp/Cntr=0.3,0.1

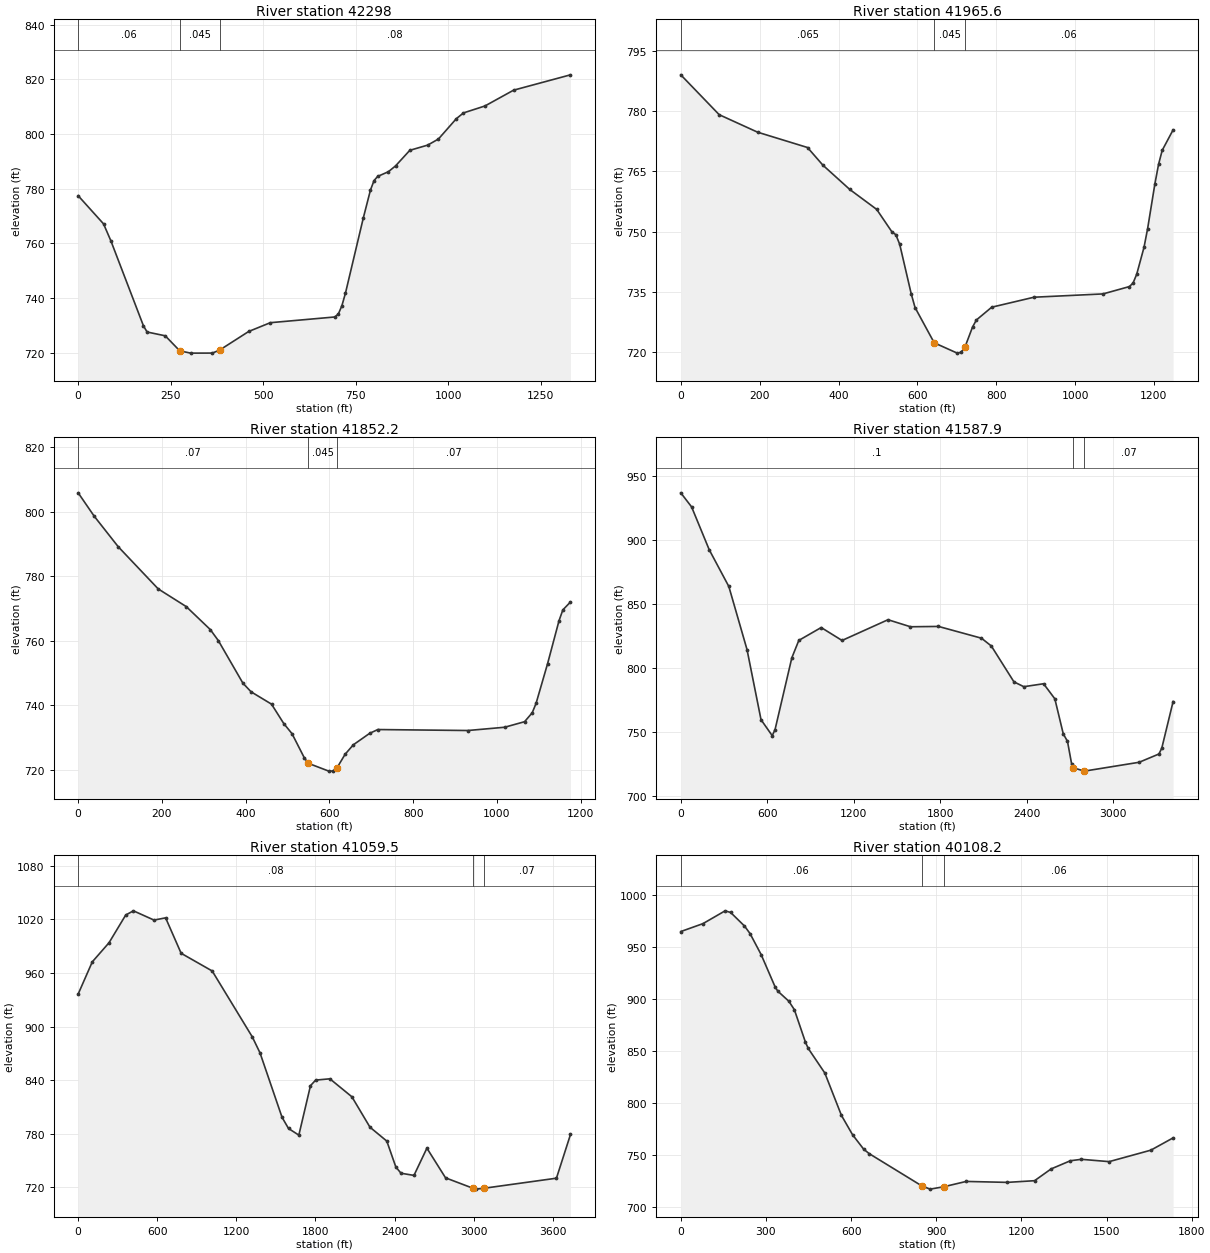
Type RM Length L Ch R = 1 ,42298   ,334.3,332.4,331.1
XS GIS Cut Line= 5
      1611095.45       329011.26     1610893.646      329457.973
     1610729.068      329818.478     1610735.594      330185.619
     1610750.388      330260.695
#Sta/Elev= 30
       0  777.42    68.6  767.11    88.2  760.97   176.5  729.76   186.3  727.53
   235.3  726.14   274.5  720.64   303.9   719.8   362.7  719.82   382.3  720.92
   460.8  727.73   519.2  730.94   693.2  733.03   702.8  734.07   712.5  737.12
   722.2  741.75   770.5  769.31   789.8  779.51   799.5  782.97   809.2  784.47
   838.2   786.2   857.5  788.32   896.1  794.03   944.5  795.94   973.4  798.16
  1021.8  805.61  1041.1  807.72  1099.1  810.26  1176.4  816.04  1330.2  821.66
#Mann= 3 , 0 , 0
       0     .06       0   274.5    .045       0   382.3     .08       0
Bank Sta=274.5,382.3
XS Rating Curve= 0 ,0
Exp/Cntr=0.3,0.1

Type RM Length L Ch R = 1 ,41965.6 ,113.4,113.4,113.4
XS GIS Cut Line= 4
     1611216.666      328737.871     1610738.566      328979.566
     1610544.523      329530.055     1610510.069      329654.538
#Sta/Elev= 30
       0     789    97.4  779.09   194.8  774.74   321.4  770.93   360.4  766.54
   428.6   760.5   496.8  755.55   535.7  749.93   545.4  749.26   555.2  746.87
   584.4  734.56   594.1  731.15   642.7  722.38   701.1  719.81   710.8  720.03
   720.6  721.29     740  726.31   749.7  728.05   788.6  731.23   895.7  733.71
  1070.8  734.53  1137.9  736.36  1147.1  737.25  1156.3  739.43  1174.8  746.11
    1184  750.79  1202.4   761.9  1211.7  766.74  1220.9  770.22  1248.6  775.32
#Mann= 3 , 0 , 0
       0    .065       0   642.7    .045       0   720.6     .06       0
Bank Sta=642.7,720.6
XS Rating Curve= 0 ,0
Exp/Cntr=0.3,0.1

Type RM Length L Ch R = 1 ,41852.2 ,263.6,264.3,264.8
XS GIS Cut Line= 4
     1610779.166      328520.857     1610672.188       328827.77
     1610431.948      329509.318     1610395.486      329631.968
#Sta/Elev= 30
       0  805.81    38.2   798.6    95.6  789.14   191.2  776.07   258.1   770.6
   315.5  763.49   334.8  760.06   393.4   746.9   412.9  744.23   461.7  740.41
     491   734.4   510.6  731.28   539.9  723.83   549.6   722.1   598.5  719.68
   608.2   719.7   618.5720.7925   637.5  724.91     657  727.82   696.1  731.38
   715.6  732.55   930.5  732.25  1018.4  733.26    1066  734.98  1084.2  737.74
  1093.4  740.64  1120.8  752.89  1148.2  766.23  1157.4  769.59  1175.6  772.03
#Mann= 3 , 0 , 0
       0     .07       0   549.6    .045       0   618.5     .07       0
Bank Sta=549.6,618.5
XS Rating Curve= 0 ,0
Exp/Cntr=0.3,0.1

Type RM Length L Ch R = 1 ,41587.9 ,550.2,528.4,506.6
XS GIS Cut Line= 6
     1611645.614      326587.616     1611164.807        327381.4
     1610841.795      328292.824        1610425.      328755.232
     1610188.888      329375.024     1610188.888      329600.718
#Sta/Elev= 30
       0  936.77      75  925.79   197.4  892.31   333.4  863.64   459.7  814.34
   556.8   759.6   634.5  747.13     654  751.81   770.6  807.93   819.1  821.53
   974.3  831.57    1119  821.47    1438  837.67    1594  832.17  1788.2  832.43
  2086.5  823.24    2155  817.14  2311.8  789.14  2380.4  785.37  2517.5  787.67
  2595.6  775.91  2654.1  748.54  2683.4  742.68  2712.6  724.74  2722.4  722.09
  2800.4  719.43  3180.8  726.35  3318.1  732.82  3337.8  737.42  3416.3  773.79
#Mann= 3 , 0 , 0
       0      .1       0  2722.4    .045       0  2800.4     .07       0
Bank Sta=2722.4,2800.4
XS Rating Curve= 0 ,0
Exp/Cntr=0.3,0.1

Type RM Length L Ch R = 1 ,41059.5 ,970.5,951.3,931.7
XS GIS Cut Line= 6
     1609909.813      326041.741     1609613.576       328679.91
     1609633.964      328701.775       1609730.3      328814.079
     1610059.115       329293.96     1610078.646       329612.97
#Sta/Elev= 30
       0  936.32   107.2  972.38     234  993.75   360.8 1024.81   419.2 1029.49
   575.2 1019.14   663.3 1021.62     781  981.97  1016.5  962.17  1320.6  888.42
  1379.4  870.44  1546.2  798.42  1595.3   785.9  1673.7  778.44    1762  833.82
  1801.3  840.04  1909.2  841.48    2076  821.35  2213.3   787.3  2340.8  771.78
  2409.5  742.73  2448.7   735.8  2546.8  733.37  2644.9  763.86  2786.4  730.64
  2997.4  718.81  3016.8  718.01    3075  718.93  3627.4  730.24  3733.9  779.16
#Mann= 3 , 0 , 0
       0     .08       0  2997.4    .045       0    3075     .07       0
Bank Sta=2997.4,3075
XS Rating Curve= 0 ,0
Exp/Cntr=0.3,0.1

Type RM Length L Ch R = 1 ,40108.2 ,1213.2,1196.2,1178.9
XS GIS Cut Line= 5
     1608245.521      329468.105     1609292.396      329593.105
       1609482.5      329621.751     1609667.396      329707.688
     1609943.437       329639.98
#Sta/Elev= 30
       0   964.8    78.1  972.41   156.2  984.73   175.7  983.15   224.5  970.11
     244  962.88   283.1  942.68   331.9  911.87   341.7  907.52   380.7  897.82
   400.2  889.68   439.3  858.37   449.1  852.39   507.6  828.72   566.2  787.94
   605.2  769.42   644.3  755.55   663.8  751.24   849.3   720.2   878.6   717.1
   927.4  719.42  1005.5   724.5  1150.4  723.59  1246.6  725.21  1304.8  736.52
  1372.8   744.4  1411.6  745.77  1509.3  743.54  1656.3  754.57  1734.7  766.38
#Mann= 3 , 0 , 0
       0     .06       0   849.3    .045       0   927.4     .06       0
Bank Sta=849.3,927.4
XS Rating Curve= 0 ,0
Exp/Cntr=0.3,0.1