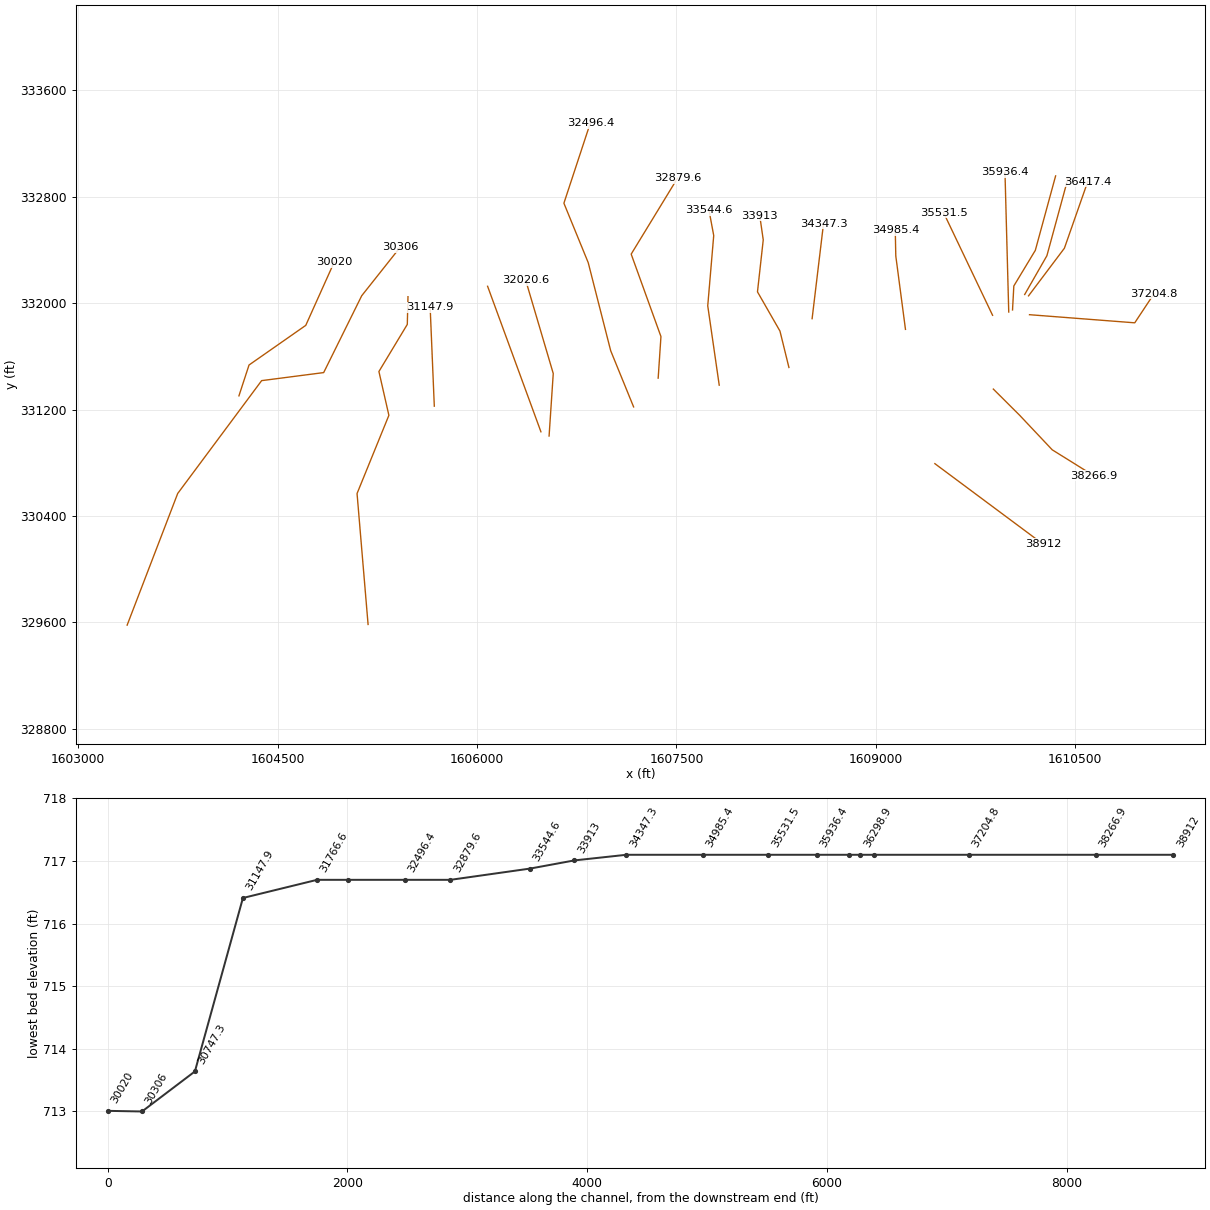
HEC-RAS study MCLRYCRK.prj: MCLRYCRK

--- MCLRYCRK.g01 (geometry) --- (continued)

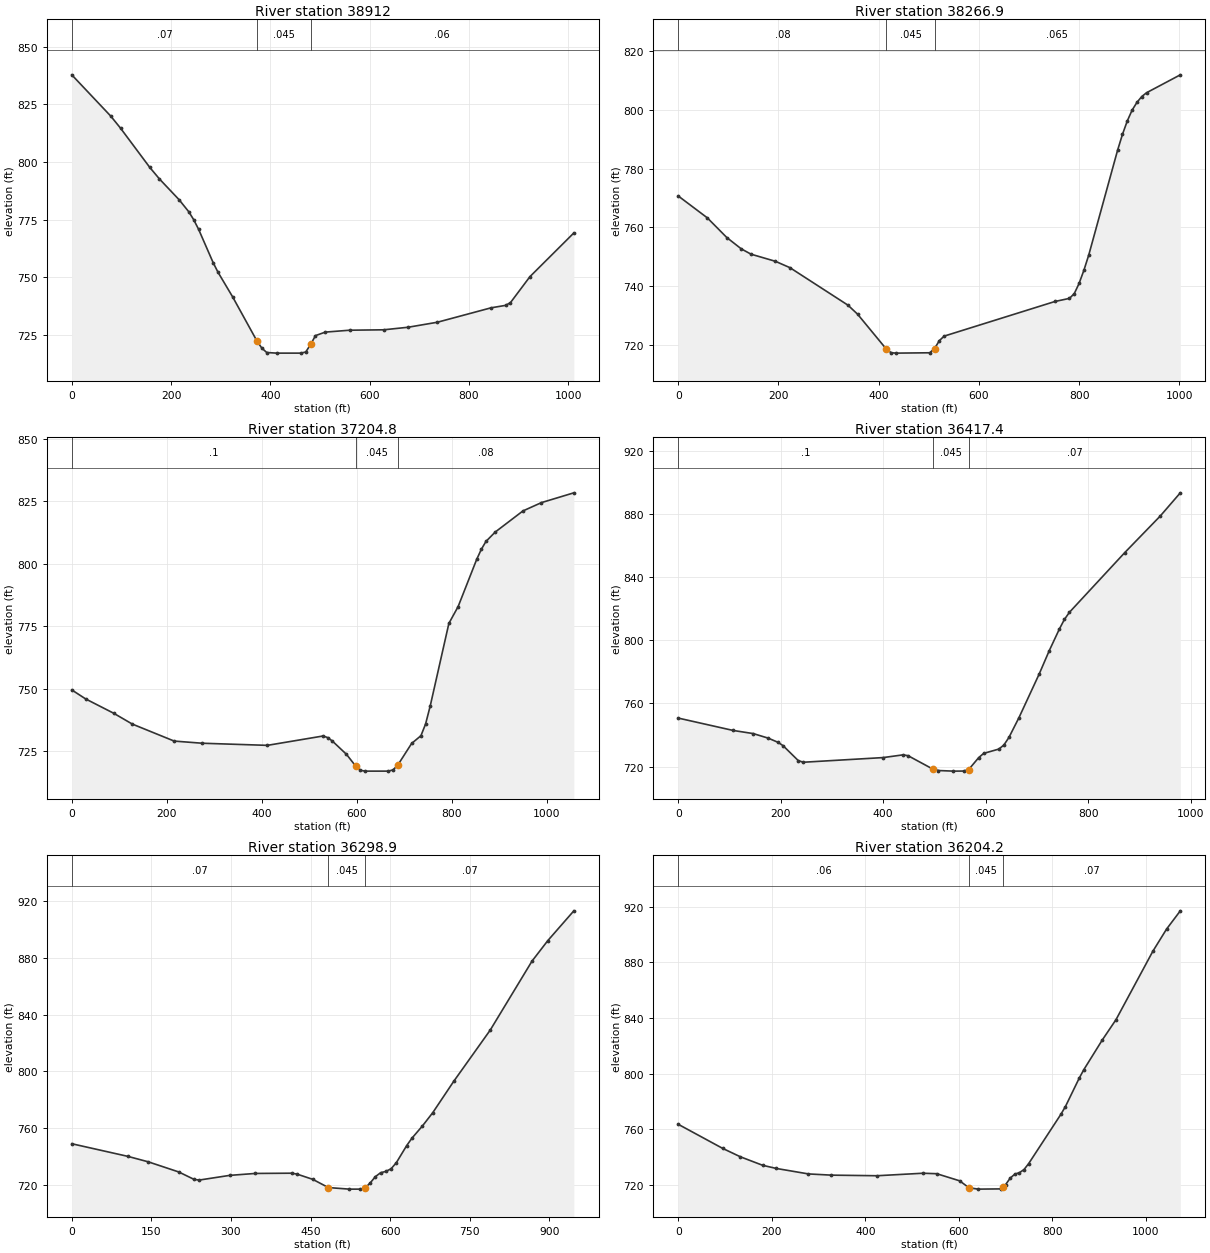
Type RM Length L Ch R = 1 ,38912   ,649,645.1,641.2
XS GIS Cut Line= 2
     1609444.305      330793.626     1610255.937      330190.327
#Sta/Elev= 30
       0  837.84    78.6  819.91    98.2   814.7   157.1  797.68   176.7  792.64
     216   783.7   235.6  778.46   245.5  775.02   255.3   770.9   284.7  756.39
   294.6  752.17     324  741.52   373.1  722.32   382.9  719.25   392.7  717.37
   412.4   717.1   461.5   717.1   471.3   717.6   481.1  720.86   490.9   724.7
   510.6  726.22   559.6  727.04   628.4  727.22   677.5  728.33   736.4   730.5
   844.4  736.75   873.8  737.82   883.6     739   922.9  750.29  1011.3  769.24
#Mann= 3 , 0 , 0
       0     .07       0   373.1    .045       0   481.1     .06       0
Bank Sta=373.1,481.1
XS Rating Curve= 0 ,0
Exp/Cntr=0.3,0.1

Type RM Length L Ch R = 1 ,38266.9 ,1045.4,1062.1,1078.7
XS GIS Cut Line= 4
     1609884.117      331354.343     1610083.179      331156.122
     1610327.127      330897.692     1610637.457       330704.55
#Sta/Elev= 30
       0  770.69    58.1  763.22    96.9  756.52   125.9  752.64   145.3  750.84
   193.7  748.42   222.8  746.25   338.6  733.46   357.8  730.39   415.4  718.44
     425  717.23   434.6   717.1   501.8  717.22   511.4  718.65     521  721.36
   530.6   722.9   751.7  734.71   780.6  735.77   790.2  737.39   799.8  740.85
   809.4  745.34   819.1  750.55   876.8  786.38   886.4   791.7     896  796.28
   905.6  799.95   915.3  802.61   924.9   804.6   934.5   805.9  1001.8     812
#Mann= 3 , 0 , 0
       0     .08       0   415.4    .045       0   511.4    .065       0
Bank Sta=415.4,511.4
XS Rating Curve= 0 ,0
Exp/Cntr=0.3,0.1

Type RM Length L Ch R = 1 ,37204.8 ,757.7,787.4,816.8
XS GIS Cut Line= 3
     1610156.214      331913.506     1610947.782       331852.46
     1611093.186      332071.737
#Sta/Elev= 30
       0  749.56    29.4  745.94    88.2  740.24   127.4  735.91   215.6  729.11
   274.4  728.25   411.7   727.4   529.3  731.15   539.1  730.48   548.9  729.07
   578.3  723.82   597.9  719.07   607.7  717.44   617.5   717.1   666.5   717.1
   676.3   717.6   686.1  719.44   715.5  728.16   735.1  731.26   744.9  735.95
   754.7   743.2   793.9  776.14   813.4  782.87   852.4   801.7   862.1   805.7
   871.9  808.89   891.4  812.64   949.8  821.09   988.8  824.42    1057  828.33
#Mann= 3 , 0 , 0
       0      .1       0   597.9    .045       0   686.1     .08       0
Bank Sta=597.9,686.1
XS Rating Curve= 0 ,0
Exp/Cntr=0.3,0.1

Type RM Length L Ch R = 1 ,36417.4 ,116.9,118.5,120.1
XS GIS Cut Line= 3
     1610148.854      332055.149     1610418.668      332413.314
     1610594.409       332914.63
#Sta/Elev= 30
       0  750.74   107.2  742.89   146.2  740.92   175.5  738.03     195  735.32
   204.7  733.19     234  723.84   243.7  722.73   399.7  725.69   438.7  727.42
   448.4  726.89   497.6  718.25   507.4  717.48     537   717.1   556.6  717.15
   566.5  718.04   586.2  725.66     596  728.36   625.5  731.08   635.3  733.63
   645.2  738.45   664.8  751.02   704.2  778.65   723.9  793.51   743.6   807.2
   753.4  813.27   763.2  817.81   871.4  855.75   940.3  878.83   979.6   893.6
#Mann= 3 , 0 , 0
       0      .1       0   497.6    .045       0   566.5     .07       0
Bank Sta=497.6,566.5
XS Rating Curve= 0 ,0
Exp/Cntr=0.3,0.1

Type RM Length L Ch R = 1 ,36298.9 ,94.8,94.8,94.8
XS GIS Cut Line= 3
     1610120.023      332065.394      1610286.99      332356.979
     1610447.505       332945.64
#Sta/Elev= 30
       0  749.06   105.6  740.18     144  736.34   201.6  729.19   230.4  723.97
     240  723.47   297.6  726.78   345.8  728.14   414.7  728.32   424.6  727.66
   454.1     724   483.6   718.2     523   717.1   542.7   717.1   552.5  717.84
   562.4  721.45   572.2   725.9     582  728.63   591.9  729.58   601.7  731.42
   611.6  735.68   631.2  747.76   641.1  752.99   660.8  761.56   680.4  770.99
   719.8  792.99   788.7  829.13   867.4  877.67     897  892.03   946.2  913.06
#Mann= 3 , 0 , 0
       0     .07       0   483.6    .045       0   552.5     .07       0
Bank Sta=483.6,552.5
XS Rating Curve= 0 ,0
Exp/Cntr=0.3,0.1

Type RM Length L Ch R = 1 ,36204.2 ,261.1,267.7,274.4
XS GIS Cut Line= 4
     1610028.437      331949.177     1610038.179      332129.445
     1610199.972      332397.504     1610352.505       332956.89
#Sta/Elev= 30
       0  763.68      95  746.37     133  740.31   180.5  734.22   209.9  731.94
   278.4  728.02   327.3  727.15   425.1  726.72   523.1  728.52   552.6  728.18
   601.7  723.06   621.4   718.1     641   717.1   690.2  717.27   693.8718.4198
     700   720.4   709.8  725.05   719.7  727.89   729.5  728.93   739.3  731.19
   749.1   735.4   817.9  770.76   827.8  776.45   857.2  796.79   867.1  802.93
   906.4  824.17   935.9  838.86  1014.5  887.91    1044  903.94  1073.4  917.06
#Mann= 3 , 0 , 0
       0     .06       0   621.4    .045       0   693.8     .07       0
Bank Sta=621.4,693.8
XS Rating Curve= 0 ,0
Exp/Cntr=0.3,0.1

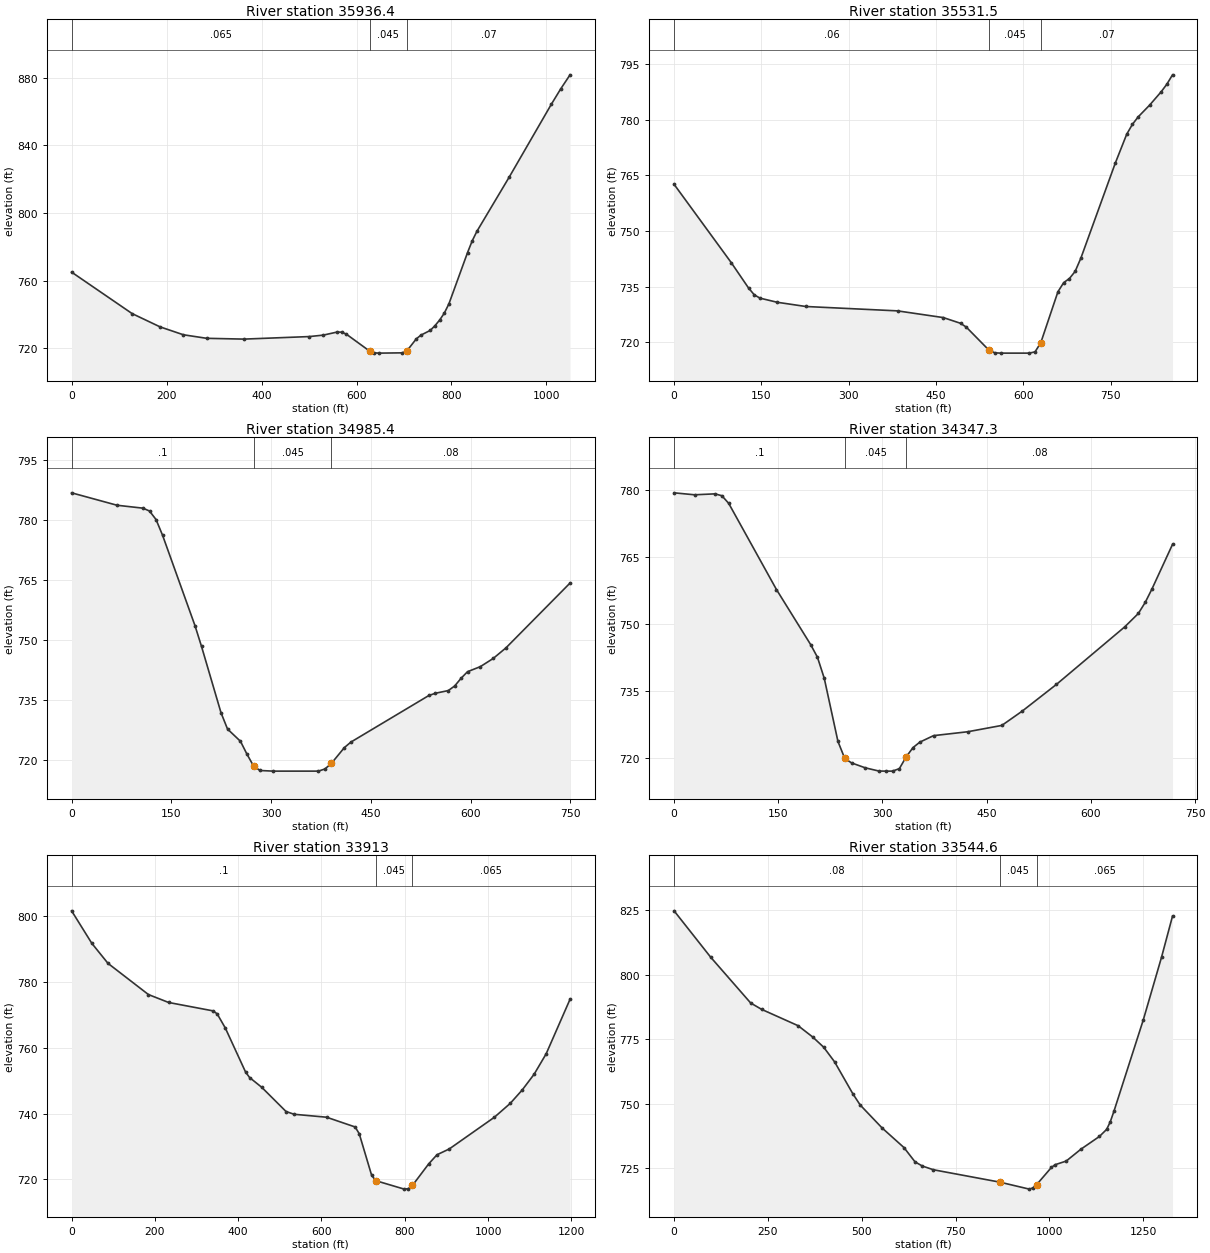
Type RM Length L Ch R = 1 ,35936.4 ,395.5,404.9,414.2
XS GIS Cut Line= 2
     1609999.965      331933.552     1609971.632      332982.857
#Sta/Elev= 30
       0  765.01   127.5  740.48   186.4  732.62   235.4  727.96   284.5  725.86
     363  725.39   500.3  726.89   529.8  727.74   559.2  729.56     569   729.5
   578.8  728.28   627.8  718.27   637.7  717.25   647.5   717.1   696.5  717.27
   706.3   718.5     726  725.56   735.8  727.76   755.4  730.56   765.2  733.32
     775  736.63   784.8   740.7   794.6  746.24   833.9  776.61   843.7  783.53
   853.5  789.11   922.2   821.5  1010.4  864.34  1030.1  873.41  1049.7   881.7
#Mann= 3 , 0 , 0
       0    .065       0   627.8    .045       0   706.3     .07       0
Bank Sta=627.8,706.3
XS Rating Curve= 0 ,0
Exp/Cntr=0.3,0.1

Type RM Length L Ch R = 1 ,35531.5 ,552.9,546.2,538.6
XS GIS Cut Line= 2
     1609878.333      331909.077     1609509.409      332681.646
#Sta/Elev= 30
       0  762.61    98.4  741.45   127.9  734.66   137.8  732.81   147.6  731.92
   177.1  730.81   226.3  729.67   383.8  728.49   462.5  726.68     492  725.14
   501.9  724.11   541.2  717.84   551.1  717.18   560.9   717.1   610.1   717.1
     620  717.45   629.8  719.89   659.3  733.65   669.2  736.11     679  737.21
   688.8  739.12   698.7  742.71   757.7  768.28   777.4   776.1   787.2  778.77
   797.1  780.78   816.8  783.96   836.4  787.51   846.3  789.58   856.1  792.12
#Mann= 3 , 0 , 0
       0     .06       0   541.2    .045       0   629.8     .07       0
Bank Sta=541.2,629.8
XS Rating Curve= 0 ,0
Exp/Cntr=0.3,0.1

Type RM Length L Ch R = 1 ,34985.4 ,643.7,638,632.7
XS GIS Cut Line= 3
     1609223.069      331803.219     1609150.261      332355.302
     1609146.354       332548.01
#Sta/Elev= 30
       0  786.72    68.4  783.61   107.5  782.88   117.2  782.16     127  780.04
   136.8  776.11   185.6  753.48   195.4  748.29   224.7  731.71   234.5  727.63
     254  724.56   263.8  721.32   273.6   718.4   283.3  717.26   302.9   717.1
   371.2   717.1     381  717.64   390.8  719.05   410.3     723   420.1  724.37
   537.3  736.02   547.1  736.58   566.5  737.25   576.1   738.4   585.8  740.34
   595.4  741.97   614.7  743.24     634  745.28   653.2  747.93   749.6  764.15
#Mann= 3 , 0 , 0
       0      .1       0   273.6    .045       0   390.8     .08       0
Bank Sta=273.6,390.8
XS Rating Curve= 0 ,0
Exp/Cntr=0.3,0.1

Type RM Length L Ch R = 1 ,34347.3 ,434.1,434.3,434.4
XS GIS Cut Line= 2
     1608520.796       331883.62     1608606.362      332595.959
#Sta/Elev= 30
       0  779.45    29.5  779.01      59  779.22    68.8   778.8    78.6   777.1
   147.4  757.78   196.6  745.45   206.4  742.61   216.2  737.89   235.9  723.75
   245.7  719.94   255.5  718.94   275.2  717.84   294.8  717.12   304.7   717.1
   314.5   717.1   324.3  717.66   334.2  720.32     344  722.38   353.8   723.6
   373.5  725.05   422.6  725.92   471.8  727.34   501.2  730.55   550.4  736.53
   648.7  749.42   668.3  752.42   678.2   754.9     688  757.94   717.5   767.9
#Mann= 3 , 0 , 0
       0      .1       0   245.7    .045       0   334.2     .08       0
Bank Sta=245.7,334.2
XS Rating Curve= 0 ,0
Exp/Cntr=0.3,0.1

Type RM Length L Ch R = 1 ,33913   ,367.8,368.4,368.9
XS GIS Cut Line= 5
     1608346.333       331516.76     1608279.058      331790.198
     1608109.788      332085.337      1608153.19      332475.962
     1608127.149      332656.083
#Sta/Elev= 30
       0  801.67    48.6  791.78    87.4  785.69   184.5   776.2     233  773.79
   339.9  771.23   349.6  770.32   369.1  766.02   417.7  752.64   427.4  750.96
   456.6  747.98   514.9  740.62   534.3  739.78   612.1  738.89   680.8  735.92
   690.6  733.88   720.1  721.35   729.9   719.6   798.7  717.01   808.5  717.14
   818.3  718.12   857.6  724.72   877.3  727.46   906.8  729.23  1014.9  738.85
  1053.2  743.09  1081.9  747.16  1110.6  751.97  1139.4  758.16  1196.8  774.77
#Mann= 3 , 0 , 0
       0      .1       0   729.9    .045       0   818.3    .065       0
Bank Sta=729.9,818.3
XS Rating Curve= 0 ,0
Exp/Cntr=0.3,0.1

Type RM Length L Ch R = 1 ,33544.6 ,655.2,665,674.4
XS GIS Cut Line= 4
     1607822.027      331383.839     1607735.656      331980.302
     1607780.631      332508.816      1607744.77      332700.354
#Sta/Elev= 30
       0  824.85    97.2  806.92   204.1  789.09   233.3  786.62   330.5  780.28
   369.4  775.89   398.6  771.94   427.7  766.25   476.3  753.87   495.8  749.53
   554.1  740.63   612.5     733     642  727.45   661.6  725.83   691.1  724.39
   867.9  719.59   946.5  716.88   956.3  717.37   966.1  718.65  1005.4  725.31
  1015.2  726.36  1044.7  727.76    1084  732.38  1133.1   737.3  1152.6  740.08
  1162.3  743.05  1172.1  747.17    1250  782.48  1298.7  806.84    1328  822.81
#Mann= 3 , 0 , 0
       0     .08       0   867.9    .045       0   966.1    .065       0
Bank Sta=867.9,966.1
XS Rating Curve= 0 ,0
Exp/Cntr=0.3,0.1

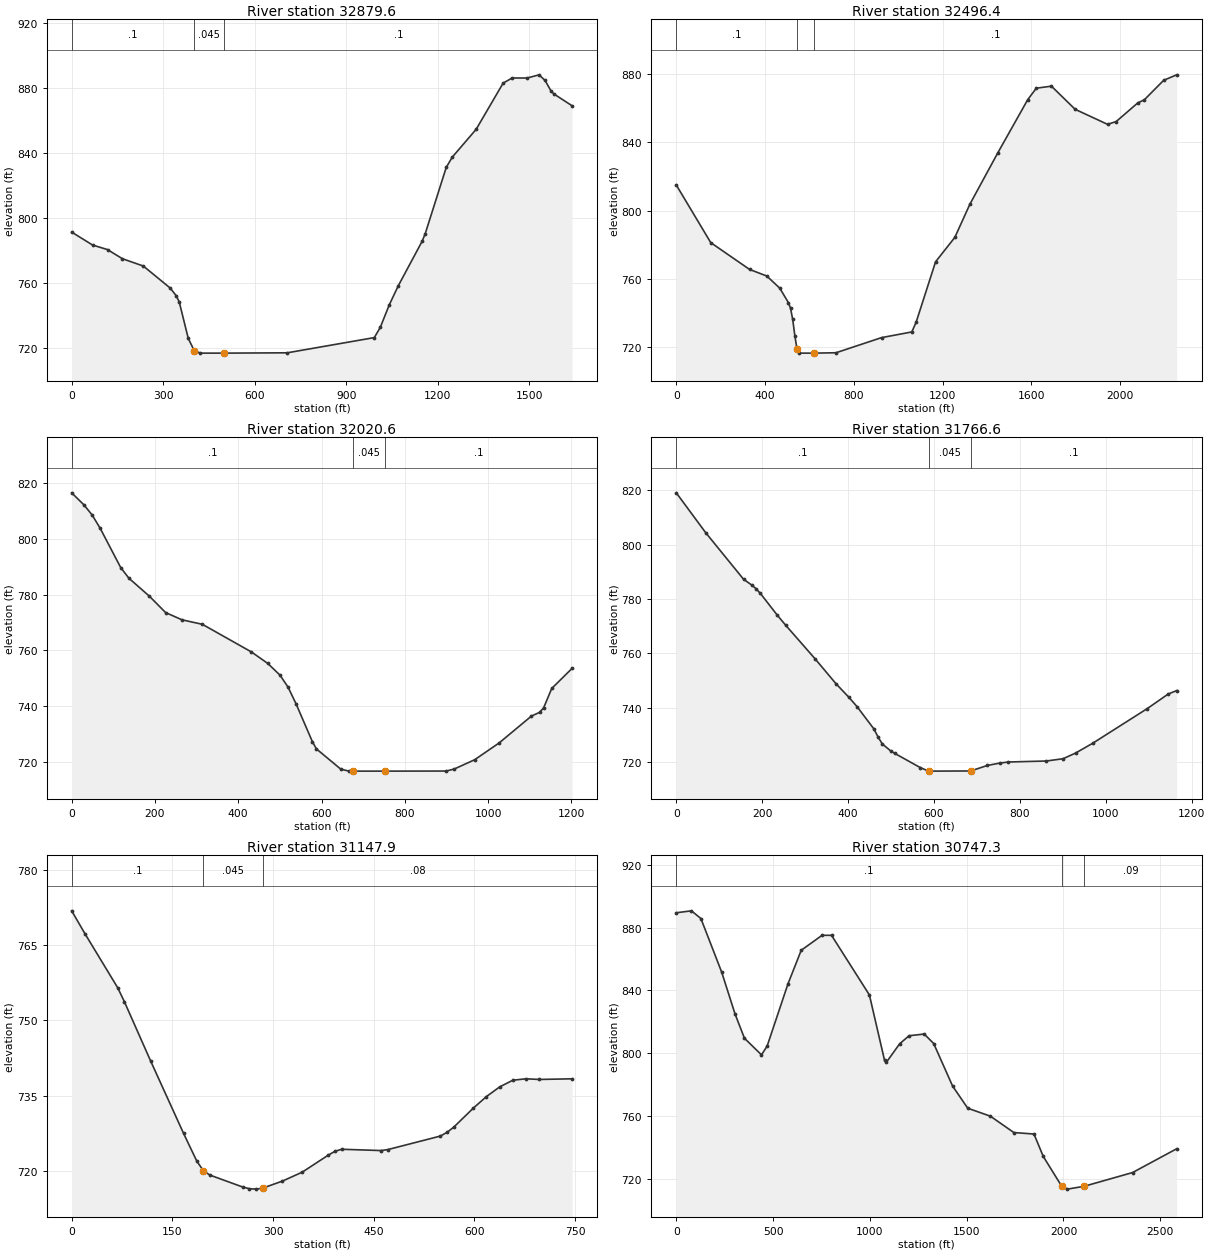
Type RM Length L Ch R = 1 ,32879.6 ,385.1,383.2,381.3
XS GIS Cut Line= 4
     1607362.826      331436.574     1607383.659      331749.074
     1607159.749      332369.039     1607507.791      332939.069
#Sta/Elev= 30
       0  791.16    68.5  783.21   117.4   780.4   166.4  774.77   234.9  770.28
     323  756.72   342.7     752   352.6  748.16   382.1  725.76   401.7  718.25
   421.4   716.7   500.7   716.7   706.7   716.9     992  726.26  1011.6  732.58
  1041.1  746.44  1070.6  758.16  1149.2  785.69    1159  790.28  1227.7  830.95
  1247.4  837.27  1325.9  854.44  1414.3  882.84  1443.8  885.98  1492.9  885.97
  1532.2  887.93  1551.8  884.44  1571.5  877.88  1581.3  876.08  1640.2   868.9
#Mann= 3 , 0 , 0
       0      .1       0   401.7    .045       0   500.7      .1       0
Bank Sta=401.7,500.7
XS Rating Curve= 0 ,0
Exp/Cntr=0.3,0.1

Type RM Length L Ch R = 1 ,32496.4 ,475,475.9,476.7
XS GIS Cut Line= 5
      1607177.93      331220.319     1607005.537      331642.731
     1606836.602      332304.681     1606653.624      332751.569
     1606851.541      333352.264
#Sta/Elev= 30
       0  814.88   155.3  781.24     330   765.6   407.7  761.73     466  754.69
     505  746.26   514.8  742.91   524.6  736.39   534.3  726.81   544.1     719
   553.8   716.7   622.2   716.7   719.7  716.92   924.7  725.75  1061.3  729.07
  1080.8  734.76  1168.4  770.05  1255.3  784.33  1322.9  803.66  1448.5  833.61
  1583.7  864.75  1622.3  871.43  1690.4  872.62  1797.4  859.09  1943.4  850.32
  1982.3  851.96  2079.6  862.86  2108.8  864.63  2196.4  876.06  2254.8  879.24
#Mann= 3 , 0 , 0
       0      .1       0   544.1    .045       0   622.2      .1       0
Bank Sta=544.1,622.2
XS Rating Curve= 0 ,0
Exp/Cntr=0.3,0.1

Type RM Length L Ch R = 1 ,32020.6 ,252.5,254,255.4
XS GIS Cut Line= 3
     1606542.167      331001.498     1606573.527      331471.306
     1606366.454      332172.168
#Sta/Elev= 30
       0  816.49    29.4  812.17      49  808.57    68.7   803.7   117.7   789.7
   137.3  785.89   186.4  779.45   225.6  773.55   264.9  770.96   313.9  769.34
   431.6  759.44   470.8  755.33   500.1  751.15   519.6  746.82   539.1  740.75
     578  727.28   587.8  724.66   646.2  717.42   665.7   716.7   675.5   716.7
   753.4   716.7   899.6  716.73   919.1  717.48   967.8  720.79  1026.3  726.78
  1104.2  736.45  1123.7  737.77  1133.5  739.43  1152.9  746.35  1201.7  753.54
#Mann= 3 , 0 , 0
       0      .1       0   675.5    .045       0   753.4      .1       0
Bank Sta=675.5,753.4
XS Rating Curve= 0 ,0
Exp/Cntr=0.3,0.1

Type RM Length L Ch R = 1 ,31766.6 ,625.6,618.7,611.7
XS GIS Cut Line= 2
     1606480.764      331033.209     1606079.722      332126.959
#Sta/Elev= 30
       0  819.12    68.5  804.44   156.6  787.32   176.2  785.12     186  783.79
   195.8   782.1     235  774.12   254.5  770.43   323.1  758.04     372  748.83
   401.4  743.95     421  740.41   460.1  732.22   469.9  729.22   479.7  726.69
   499.3  724.13   509.1  723.19   567.8  718.02   587.4   716.7   685.3  716.76
   724.4  718.79   753.8  719.68   773.4  720.06   861.5  720.42   900.6  721.27
     930  723.38   969.2  726.93  1096.4   739.7  1145.4  745.09    1165  746.34
#Mann= 3 , 0 , 0
       0      .1       0   587.4    .045       0   685.3      .1       0
Bank Sta=587.4,685.3
XS Rating Curve= 0 ,0
Exp/Cntr=0.3,0.1

Type RM Length L Ch R = 1 ,31147.9 ,412,400.6,392
XS GIS Cut Line= 2
      1605678.68      331225.917      1605647.43      331970.709
#Sta/Elev= 30
       0  771.83    19.6  767.31    68.7  756.48    78.5  753.73   117.7   741.9
   166.7   727.5   186.4  721.98   196.2  720.07     206   719.2     255  716.82
   264.8  716.49   274.6  716.41   284.4   716.6   313.9  718.01   343.3  719.78
   382.5   723.2   392.3  723.95   402.2  724.35     461  724.09   470.8  724.28
   549.3  726.98   559.1  727.72   568.9  728.72   598.3  732.54   617.9  734.85
   637.6  736.77   657.2   738.1   676.8  738.38   696.4  738.25   745.4  738.38
#Mann= 3 , 0 , 0
       0      .1       0   196.2    .045       0   284.4     .08       0
Bank Sta=196.2,284.4
XS Rating Curve= 0 ,0
Exp/Cntr=0.3,0.1

Type RM Length L Ch R = 1 ,30747.3 ,441.4,441.3,438.1
XS GIS Cut Line= 6
     1605180.519       329584.86     1605097.583      330569.073
     1605337.028      331157.061     1605262.014      331486.334
     1605475.555      331840.501     1605480.764      332048.834
#Sta/Elev= 30
       0  889.43    78.2  890.67   127.1  885.78   234.7   851.6   303.2  825.17
     352  809.63   440.1  799.05   469.4  804.68     577  844.24   645.4  865.58
     753   875.1   801.9  875.08   997.5  837.17  1075.6  795.66  1085.4  794.35
  1153.7  806.08  1202.6  811.22  1280.7  812.29  1329.6  806.27  1427.2  779.23
  1505.4  765.12  1622.6  760.03  1743.8  749.63  1847.7  748.69  1895.7  734.42
  1991.7  715.33  2020.5  713.64  2107.1  715.45  2357.2   724.2  2584.8  739.32
#Mann= 3 , 0 , 0
       0      .1       0  1991.7    .045       0  2107.1     .09       0
Bank Sta=1991.7,2107.1
XS Rating Curve= 0 ,0
Exp/Cntr=0.3,0.1

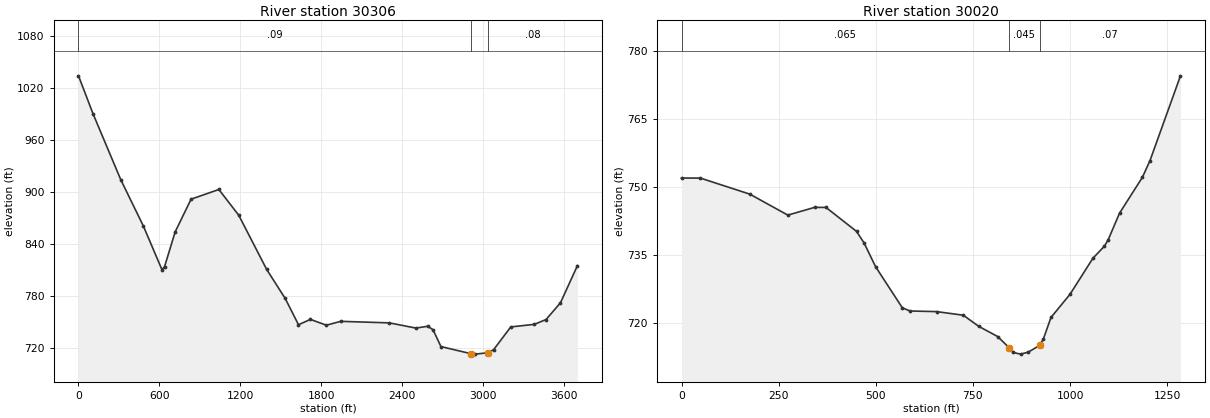
Type RM Length L Ch R = 1 ,30306   ,285,285.9,286.7
XS GIS Cut Line= 6
     1603368.019      329579.652     1603748.227      330569.235
     1604379.819      331417.868     1604846.486      331478.284
     1605132.645      332056.032     1605421.486      332419.951
#Sta/Elev= 30
       0 1034.09     108  990.21   314.1  913.99     481  860.74   618.4  810.51
     638  813.97   716.6  854.07   834.4  891.78  1040.5  902.94    1188  873.19
  1394.5  810.78  1532.2  777.19  1630.6  746.93  1719.1  753.08  1837.1  746.36
  1943.7  750.84  2304.3  749.05  2500.4  743.06  2588.6  745.15  2627.7  741.16
  2686.3  721.72    2911  713.42  2940.3     713  3037.3714.6165    3077  718.17
    3204  744.39  3378.5  747.35  3465.6  752.94  3572.1   772.2    3698  815.14
#Mann= 3 , 0 , 0
       0     .09       0    2911    .045       0  3037.3     .08       0
Bank Sta=2911,3037.3
XS Rating Curve= 0 ,0
Exp/Cntr=0.3,0.1

Type RM Length L Ch R = 1 ,30020   ,120.2,120.2,120.4
XS GIS Cut Line= 4
     1604208.986      331303.284      1604284.93      331535.265
     1604711.647      331833.247     1604924.783      332306.985
#Sta/Elev= 30
       0  751.99    48.8  751.97   175.8  748.42   273.6  743.78   342.3  745.49
   371.8  745.48   450.3  740.18     470  737.59   499.4  732.36   568.2  723.27
   587.8  722.56   656.5  722.42   725.3  721.62   764.6  719.17   813.6   716.9
     843  714.44   852.8  713.39   872.4  713.01     892  713.44   921.4  714.93
   931.2  716.36   950.8  721.13   999.8  726.26  1058.6  734.22    1088  736.88
  1097.8  738.28  1127.2  744.21    1186  752.14  1205.6  755.85    1284  774.61
#Mann= 3 , 0 , 0
       0    .065       0     843    .045       0   921.4     .07       0
Bank Sta=843,921.4
XS Rating Curve= 0 ,0
Exp/Cntr=0.3,0.1