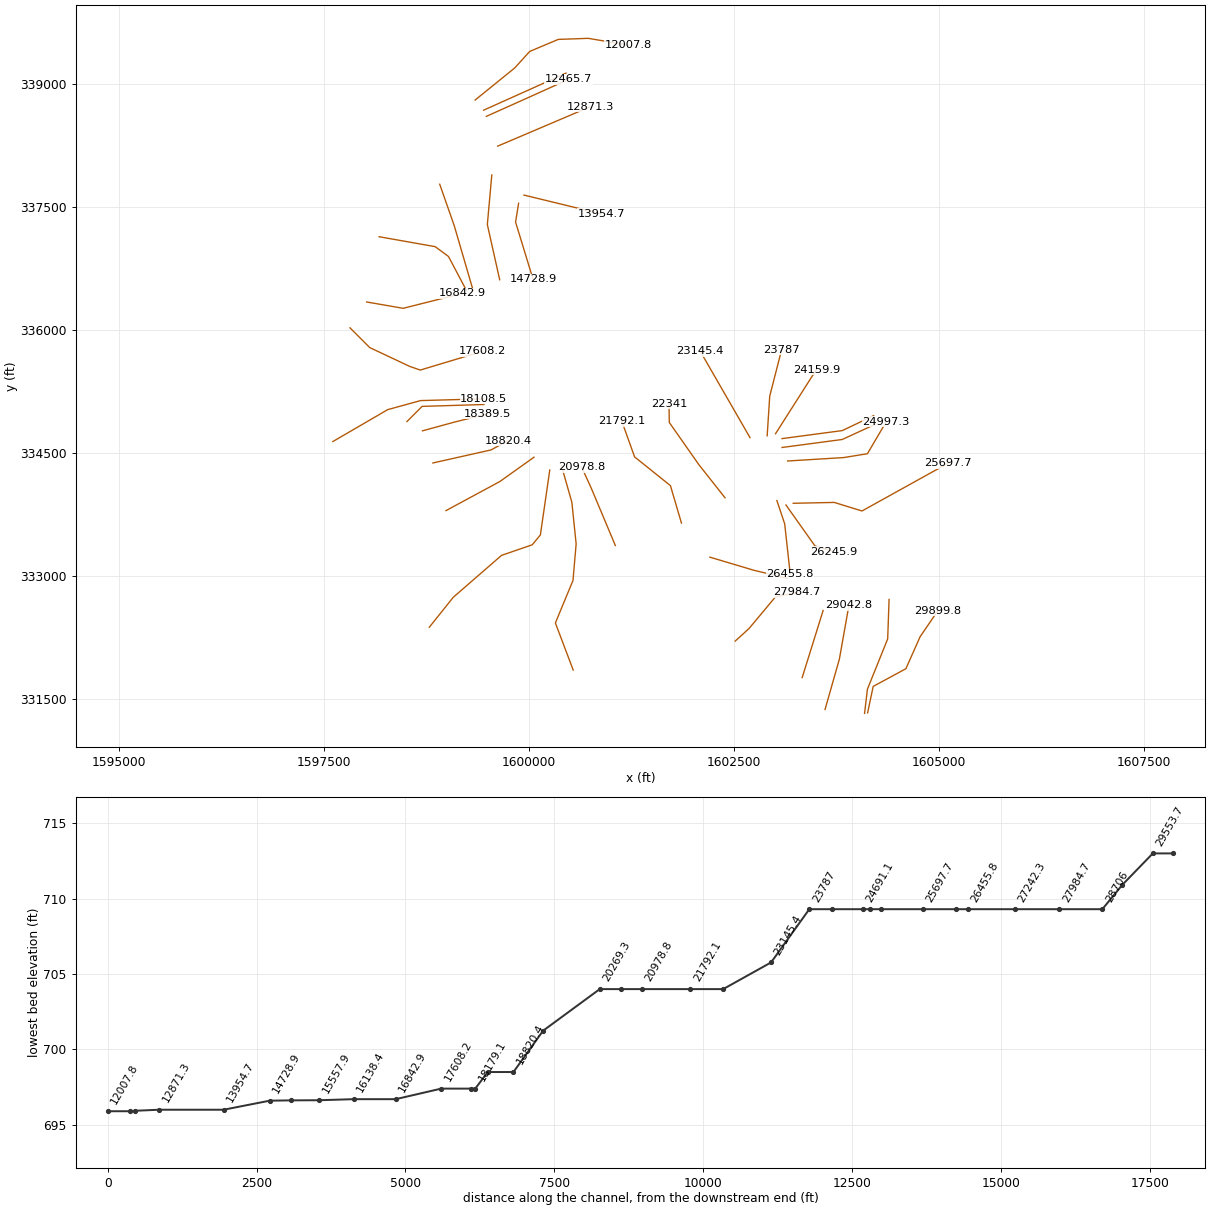
HEC-RAS study MCLRYCRK.prj: MCLRYCRK

--- MCLRYCRK.g01 (geometry) --- (continued)

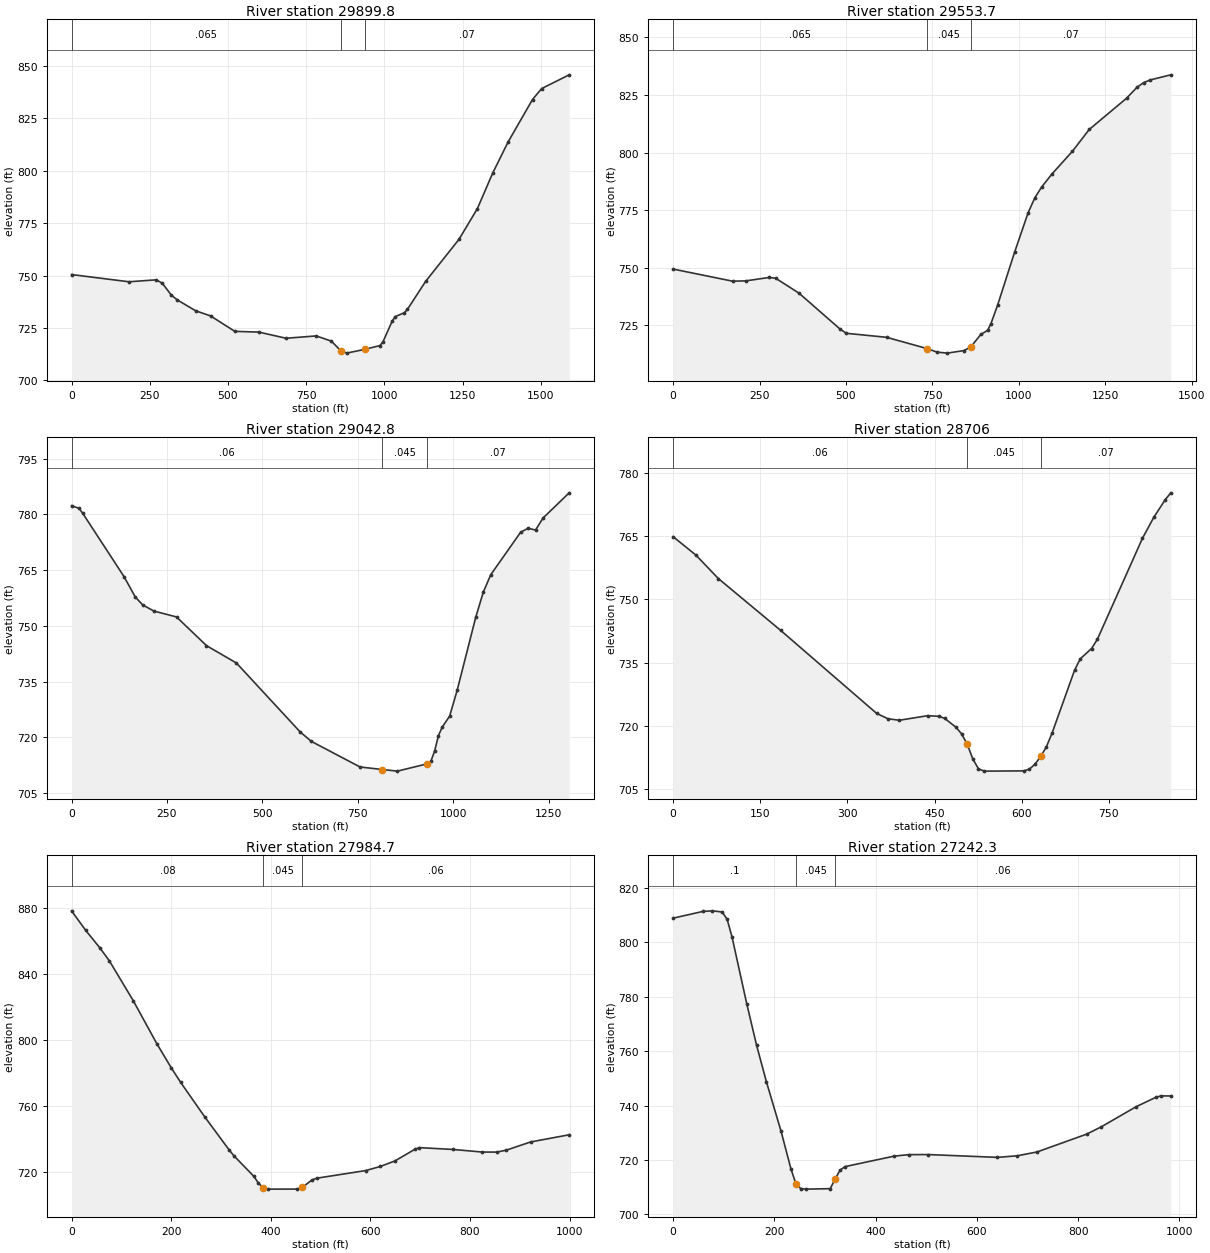
Type RM Length L Ch R = 1 ,29899.8 ,345.3,346.1,346.9
XS GIS Cut Line= 5
     1604132.935      331337.582     1604200.652      331659.534
     1604599.408      331875.041     1604772.863      332265.404
     1604988.152      332580.368
#Sta/Elev= 30
       0  750.45   183.8  747.01   270.9  747.94   290.3   746.3   319.3  740.59
   338.6  738.31   396.5  733.21   444.7  730.72   521.9  723.38     599  723.02
   685.8  720.09   782.3   721.2   830.8   718.7   859.9  714.24   879.3     713
   937.6   714.8   986.1  716.62   995.8  718.47    1025  728.25  1034.7   730.4
  1063.8  732.24  1073.5   733.8  1131.8  747.17  1238.8  767.28  1297.5  781.92
  1346.4  798.83  1395.3  813.58  1473.6  833.89  1502.9  839.12  1590.9  845.66
#Mann= 3 , 0 , 0
       0    .065       0   859.9    .045       0   937.6     .07       0
Bank Sta=859.9,937.6
XS Rating Curve= 0 ,0
Exp/Cntr=0.3,0.1

Type RM Length L Ch R = 1 ,29553.7 ,506.2,510.9,515.5
XS GIS Cut Line= 4
     1604095.435      331330.638     1604130.158      331625.082
     1604377.397      332238.837     1604394.402      332719.951
#Sta/Elev= 30
       0  749.47   172.2  744.21   210.4  744.35   277.4  745.82   296.5  745.51
   364.6  738.96   481.4  723.63   500.8  721.61   617.6  719.86   734.4  714.98
   763.6  713.44   792.8     713   841.4  714.11   860.9  715.63     890  721.12
   909.5  722.84   919.2  725.73   938.7  733.86   987.6  756.71  1026.9   773.9
  1046.6  780.47  1066.2  785.11  1095.7   790.7  1154.7  800.51  1203.8  810.06
  1311.9  823.62  1341.3  828.26    1361  830.36  1380.6  831.55  1439.6  833.75
#Mann= 3 , 0 , 0
       0    .065       0   734.4    .045       0   860.9     .07       0
Bank Sta=734.4,860.9
XS Rating Curve= 0 ,0
Exp/Cntr=0.3,0.1

Type RM Length L Ch R = 1 ,29042.8 ,339.7,336.8,333.9
XS GIS Cut Line= 3
     1603613.491       331377.86     1603788.269      331991.788
     1603904.524      332647.041
#Sta/Elev= 30
       0  782.34    19.6  781.63    29.5  780.26   137.5  763.25     167  757.77
   186.6  755.62     216  753.98     275  752.41   353.5  744.69   432.1     740
     599  721.46   628.5  718.91   755.8  712.04   814.5  711.35   853.6  710.92
   931.9  712.89   941.7  713.61   951.5  716.44   961.3  720.48   971.1  722.77
   990.6  725.72  1010.2  732.64  1059.1  752.37  1078.7  759.05  1098.3  763.77
  1176.6   775.2  1196.2  776.26  1215.7  775.79  1235.3  779.02  1303.8   785.8
#Mann= 3 , 0 , 0
       0     .06       0   814.5    .045       0   931.9     .07       0
Bank Sta=814.5,931.9
XS Rating Curve= 0 ,0
Exp/Cntr=0.3,0.1

Type RM Length L Ch R = 1 ,28706   ,730.2,721.4,712.5
XS GIS Cut Line= 2
      1603334.93      331767.584     1603590.139      332585.292
#Sta/Elev= 30
       0  764.82    38.9   760.5    77.9   754.9     185  742.64   350.4  722.96
   369.9   721.7   389.4  721.35     438  722.43   457.5  722.28   467.2  721.81
   486.7  719.72   496.4  718.14   506.2  715.68   515.9  712.17   525.6  709.85
   535.4   709.3   603.5  709.36   613.2  709.76     623  710.96   632.7  712.78
   642.5  715.07   652.2  718.28   691.1  733.24   700.9  735.92   720.3  738.34
   730.1  740.49   807.9  764.46   827.4  769.42   846.9  773.56   856.6  775.21
#Mann= 3 , 0 , 0
       0     .06       0   506.2    .045       0   632.7     .07       0
Bank Sta=506.2,632.7
XS Rating Curve= 0 ,0
Exp/Cntr=0.3,0.1

Type RM Length L Ch R = 1 ,27984.7 ,768.5,742.3,716.1
XS GIS Cut Line= 4
     1602517.885      332212.009     1602687.156      332365.655
     1603006.948      332748.988     1603272.573      332804.978
#Sta/Elev= 30
       0  878.33    28.6   866.4    57.2  855.71    76.2  847.82   123.8  823.82
   171.4  797.56     200  783.09   219.1  774.13   267.8  753.04   316.7     733
   326.5  729.41   365.6  717.23   375.4  712.94   385.2  709.92     395   709.3
   453.7  709.34   463.5  710.42   483.1  714.95   492.9  715.96   590.8  720.58
   620.1  723.07   649.5  726.44   688.7  733.38   698.4  734.51   766.6  733.38
   824.8  731.82   853.8  731.79   873.2  732.98   921.7  737.94   999.3  742.32
#Mann= 3 , 0 , 0
       0     .08       0   385.2    .045       0   463.5     .06       0
Bank Sta=385.2,463.5
XS Rating Curve= 0 ,0
Exp/Cntr=0.3,0.1

Type RM Length L Ch R = 1 ,27242.3 ,813.1,786.6,760.1
XS GIS Cut Line= 3
     1602209.177      333235.504      1602748.18      333074.938
     1603157.208      332976.766
#Sta/Elev= 30
       0  808.79    58.2  811.24    77.6  811.48      97  811.05   106.7  808.33
   116.4  801.82   145.4  777.36   164.8  762.13   184.2  748.75   213.3  730.46
   232.7  716.74   242.4  711.32   252.1   709.5   261.8   709.3   310.3  709.47
     320  713.03   329.7  716.28   339.4  717.56   436.4  721.41   465.4  721.96
   504.2  721.99   640.7  720.96   679.8  721.54   718.9  722.95   816.8  729.49
   846.1  732.21   914.6  739.57   953.7  743.03   963.5  743.54     983   743.5
#Mann= 3 , 0 , 0
       0      .1       0   242.4    .045       0     320     .06       0
Bank Sta=242.4,320
XS Rating Curve= 0 ,0
Exp/Cntr=0.3,0.1

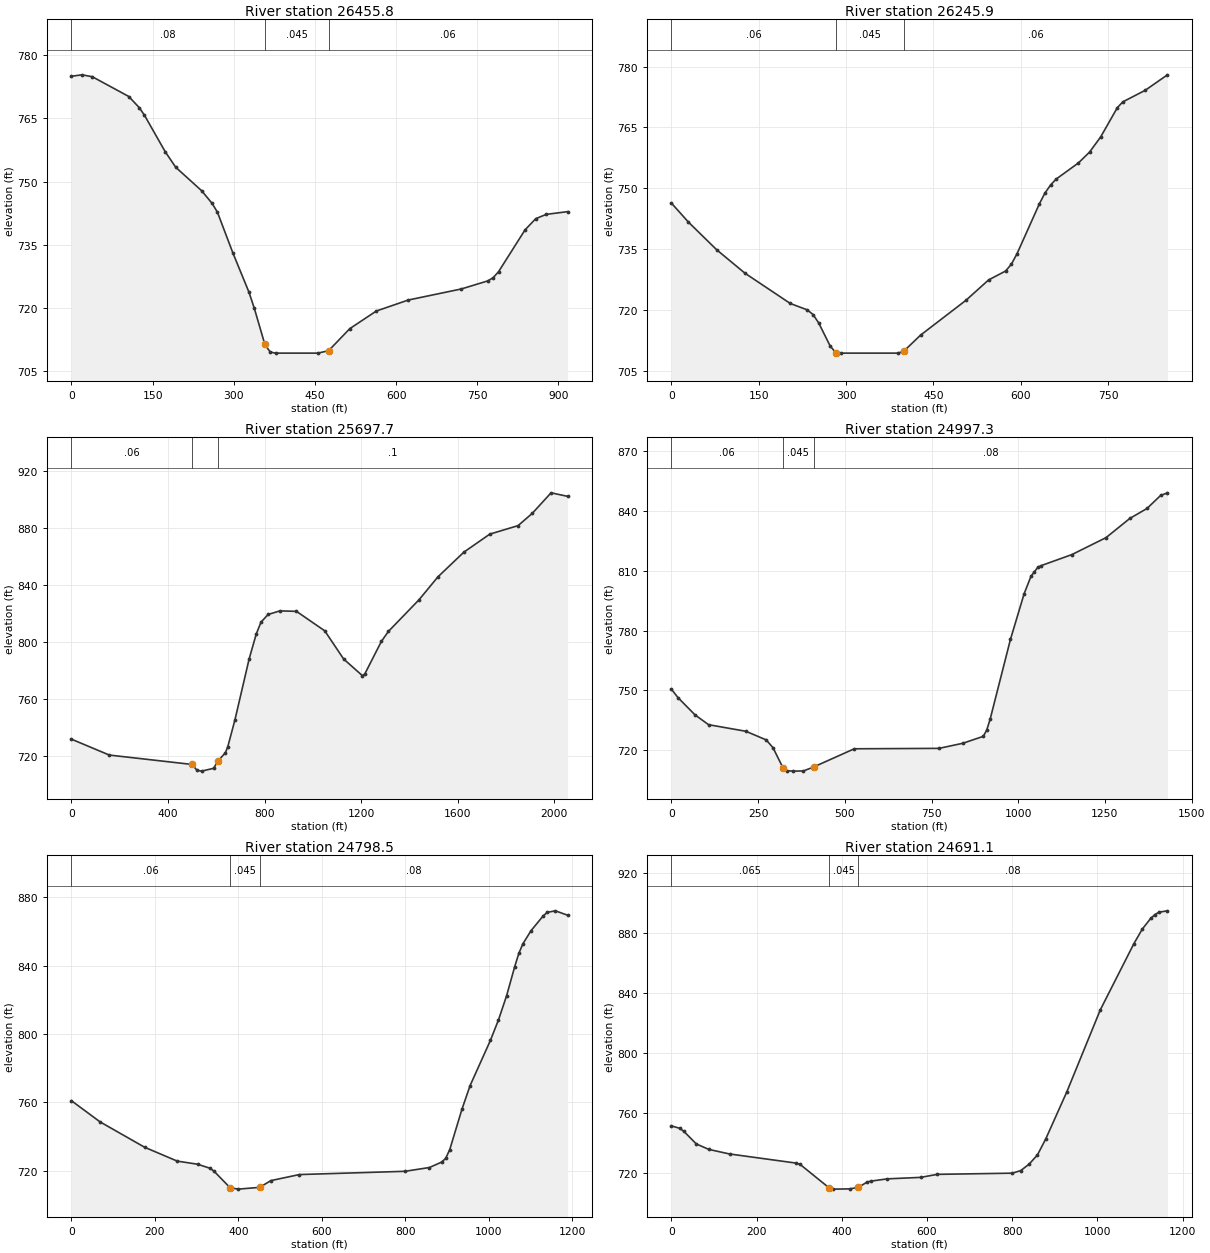
Type RM Length L Ch R = 1 ,26455.8 ,198.1,209.9,221.5
XS GIS Cut Line= 3
     1603026.198      333925.666     1603121.389      333642.584
     1603189.097      333028.001
#Sta/Elev= 30
       0  774.96    19.3   775.3    38.5  774.85     106  770.16   125.2  767.53
   134.9  765.72   173.4  757.04   192.7  753.38   240.8  747.79   260.1  744.79
   269.8  742.72   298.7  732.95   328.1  723.75   337.9  719.96   357.5  711.35
   367.4  709.56   377.2   709.3   455.7   709.3   475.3  709.88   514.6  715.12
   563.6  719.29   622.5  721.89   720.7  724.52   769.8  726.44   779.6  727.21
   789.4   728.6   838.4  738.53   858.1  741.18   877.7  742.21     917  742.85
#Mann= 3 , 0 , 0
       0     .08       0   357.5    .045       0   475.3     .06       0
Bank Sta=357.5,475.3
XS Rating Curve= 0 ,0
Exp/Cntr=0.3,0.1

Type RM Length L Ch R = 1 ,26245.9 ,533.6,548.2,562.8
XS GIS Cut Line= 3
     1603137.014      333871.751      1603491.18      333371.751
     1603720.347      333304.042
#Sta/Elev= 30
       0  746.34    29.2  741.65    77.8  734.81   126.4  729.02   204.2  721.55
   233.4  719.97   243.2  718.83   252.9  716.77   272.3  711.15     282  709.44
   291.8   709.3     389   709.3   398.8  709.75   427.9  713.75   505.7  722.33
   544.6  727.36   573.8  729.56   583.6  731.22   593.3  733.79   631.8  746.14
   641.4  748.81     651  750.78   660.5  752.24   698.8  756.23   717.9   758.9
     737  762.64   765.7  769.89   775.2  771.32   813.4  774.15   851.7  777.98
#Mann= 3 , 0 , 0
       0     .06       0     282    .045       0   398.8     .06       0
Bank Sta=282,398.8
XS Rating Curve= 0 ,0
Exp/Cntr=0.3,0.1

Type RM Length L Ch R = 1 ,25697.7 ,692.5,700.4,708.2
XS GIS Cut Line= 4
     1603225.555      333892.584     1603725.555      333903.001
     1604064.104      333798.763     1605114.993      334381.337
#Sta/Elev= 30
       0  731.72   156.9  720.57   500.1  713.98   519.8  709.95   539.5   709.3
   588.7  711.28   608.4  716.61   637.9  722.21   647.7  726.36   677.2  745.12
   736.3  788.07   765.8  805.56   785.5   813.9     815  819.27   864.1   821.8
   932.5  821.45  1049.7  807.77  1127.9  788.01    1206  776.26  1215.8  777.58
  1284.2  800.32  1313.5  807.38  1440.5  829.62  1518.6  845.66  1626.1     863
  1733.5  875.65  1850.8  881.62  1909.4   890.2  1987.5  904.65  2055.9  902.19
#Mann= 3 , 0 , 0
       0     .06       0   500.1    .045       0   608.4      .1       0
Bank Sta=500.1,608.4
XS Rating Curve= 0 ,0
Exp/Cntr=0.3,0.1

Type RM Length L Ch R = 1 ,24997.3 ,197.2,198.8,200.4
XS GIS Cut Line= 4
     1603157.847      334408.209     1603840.139      334449.876
     1604130.506      334496.887     1604359.785      334886.979
#Sta/Elev= 30
       0  750.54    19.5  746.19    68.4  737.55   107.4  732.64   214.8  729.34
   273.4     725     293  721.08   322.2  710.82     332  709.52   351.6   709.3
   380.8  709.39   410.1  711.38   527.3  720.53   771.8  720.74   840.4  723.31
   899.3  726.79   909.1  729.89   918.9  735.33   977.7  775.61  1017.1  798.53
  1036.7  807.24  1046.6  809.53  1056.4  811.73  1066.2  812.63  1154.8  818.18
  1253.1  826.69    1322  836.38  1371.2  841.35  1410.5   847.9  1430.2  849.22
#Mann= 3 , 0 , 0
       0     .06       0   322.2    .045       0   410.1     .08       0
Bank Sta=322.2,410.1
XS Rating Curve= 0 ,0
Exp/Cntr=0.3,0.1

Type RM Length L Ch R = 1 ,24798.5 ,107.4,107.4,107.4
XS GIS Cut Line= 3
     1603089.619      334573.047     1603824.232       334670.76
     1604231.045       334858.49
#Sta/Elev= 30
       0  760.97    68.3  748.65   175.5  733.76   253.5  725.68   302.3  723.86
   331.5  721.54   341.3  719.88   380.3  710.11   399.8   709.3   451.2710.3424
   477.8  714.27   546.1  717.81   799.5  719.72     858  721.94   887.2   725.1
   896.9  727.25   906.7  732.41   935.9  755.96   955.4   769.8  1004.1  796.21
  1023.5  808.21    1043  822.37  1062.5  839.43  1072.2  847.05    1082  852.69
  1101.5  860.37  1130.7  869.03  1140.4  871.09  1159.9  871.98  1189.1  869.42
#Mann= 3 , 0 , 0
       0     .06       0   380.3    .045       0   451.2     .08       0
Bank Sta=380.3,451.2
XS Rating Curve= 0 ,0
Exp/Cntr=0.3,0.1

Type RM Length L Ch R = 1 ,24691.1 ,511.5,531.3,550.8
XS GIS Cut Line= 3
     1603089.619      334681.326     1603824.232      334779.039
     1604206.045      334961.267
#Sta/Elev= 30
       0  751.45    19.5  749.84    29.2  747.84    58.5  739.43    87.8  735.78
   136.5  732.73   292.5  726.66   302.3  725.74   370.5  710.08   380.3   709.3
   419.3  709.46   439.1 710.559   458.3   713.8     468  714.63   507.1  716.15
   585.1  717.13   624.1  719.14   800.1  719.93   819.8  721.64   839.5  725.93
   859.2  732.12   878.8  742.88     928  774.09  1006.7  828.82  1085.4  872.86
  1105.1  882.57  1124.8  889.67  1134.6  892.22  1144.5  893.85  1164.2  894.75
#Mann= 3 , 0 , 0
       0    .065       0   370.5    .045       0   439.1     .08       0
Bank Sta=370.5,439.1
XS Rating Curve= 0 ,0
Exp/Cntr=0.3,0.1

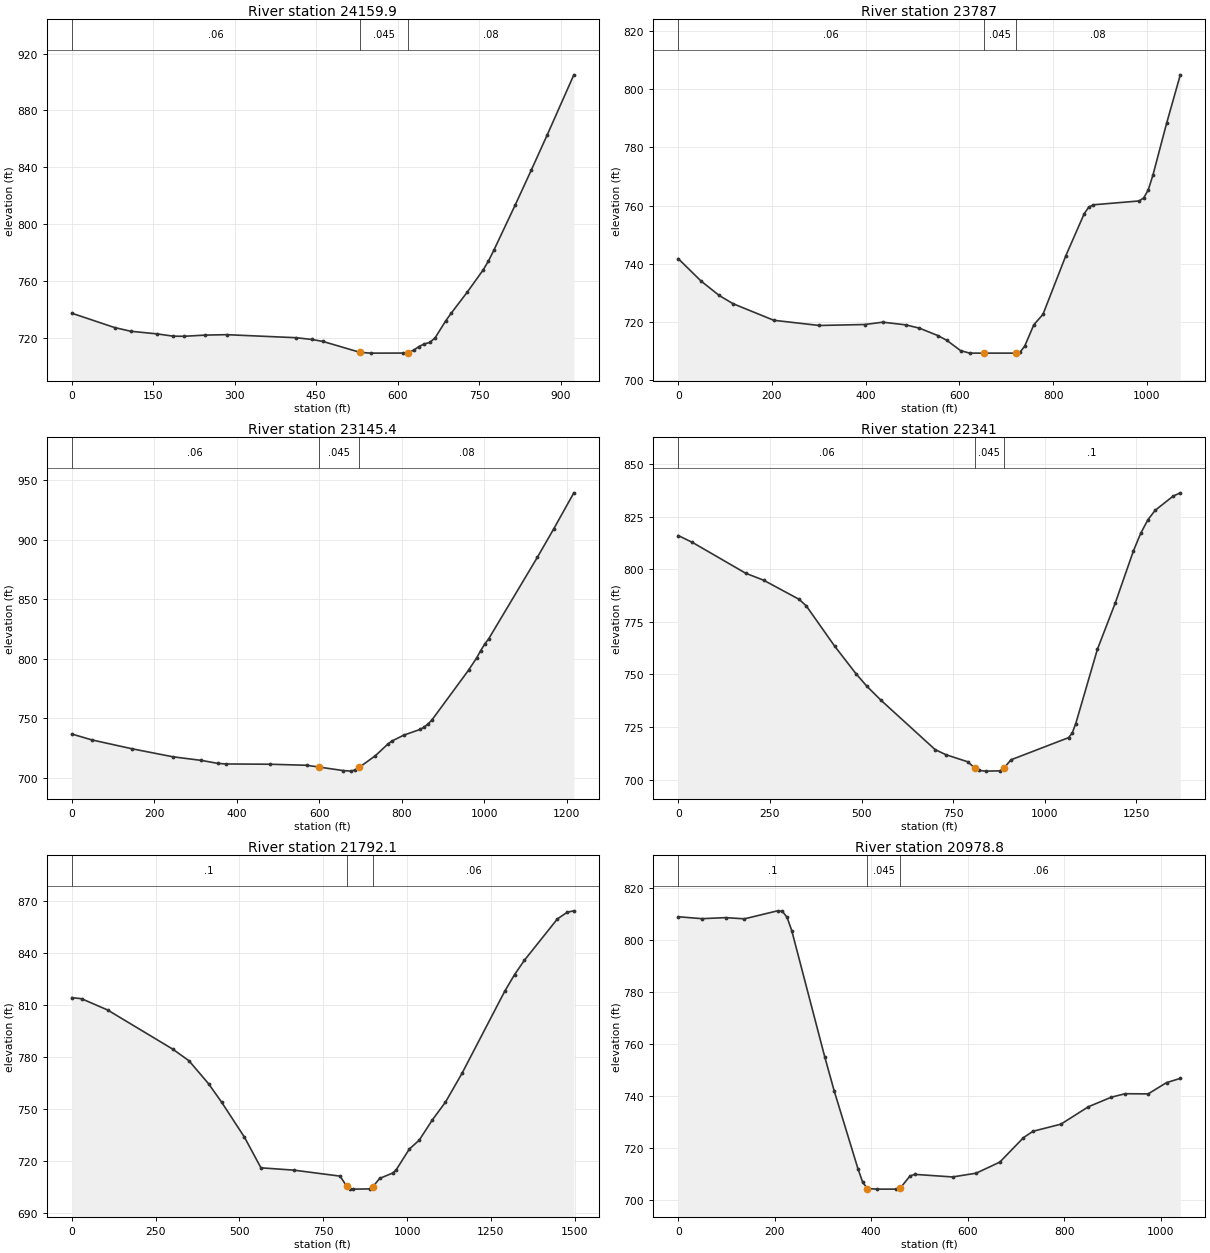
Type RM Length L Ch R = 1 ,24159.9 ,365.7,372.8,380
XS GIS Cut Line= 2
     1603009.836      334740.955     1603506.364      335520.469
#Sta/Elev= 30
       0  737.38    78.7  727.31   108.2   724.7   157.3  722.82   186.8  721.23
   206.5  721.14   245.8  721.98   285.1  722.28     413  720.14   442.4  718.89
   462.1  717.54   530.9  709.81   550.6   709.3   609.6  709.35   619.4  709.64
   629.3  711.39   639.1  713.95   648.9  715.74   658.8   716.8   668.6  719.91
   688.2  731.91   698.1  737.21   727.6     752   757.1  767.71   766.9  774.02
   776.7  781.48   816.1  813.36   845.6  837.81   875.1  862.69   924.2  905.03
#Mann= 3 , 0 , 0
       0     .06       0   530.9    .045       0   619.4     .08       0
Bank Sta=530.9,619.4
XS Rating Curve= 0 ,0
Exp/Cntr=0.3,0.1

Type RM Length L Ch R = 1 ,23787   ,624.2,641.6,659.1
XS GIS Cut Line= 3
     1602907.847      334715.501     1602939.097      335199.876
      1603084.93      335767.584
#Sta/Elev= 30
       0  741.76    48.5  734.09    87.4  729.11   116.5  726.31   203.9  720.58
   300.9   718.8     398  719.13   436.8  719.93   485.4  719.01   514.7  717.88
   553.8  715.35   573.3  713.69   602.6  710.15   622.2   709.3   651.5   709.3
   719.8   709.3   729.6  709.66   739.4  711.69   758.9  719.05   778.4  722.62
   827.3  742.81   866.4  757.19   876.1  759.45   885.9  760.25   983.6  761.57
   993.4  762.63  1003.1  765.37  1012.9  770.36  1042.2  788.22  1071.5  804.89
#Mann= 3 , 0 , 0
       0     .06       0   651.5    .045       0   719.8     .08       0
Bank Sta=651.5,719.8
XS Rating Curve= 0 ,0
Exp/Cntr=0.3,0.1

Type RM Length L Ch R = 1 ,23145.4 ,802.3,804.3,806.3
XS GIS Cut Line= 2
     1602698.646      334692.931     1602091.007      335747.619
#Sta/Elev= 30
       0  736.93    49.1  731.94   147.2  724.45   245.4  717.79   314.1  714.78
   353.4  712.31     373  711.79     481  711.56   569.3  710.68   598.8  709.23
   657.7  706.25   677.3  705.77   687.1  706.81     697  708.95   736.2  718.76
   765.7   728.3   775.5  730.93   804.9  735.97   844.2  740.75     854  742.64
   863.8  745.34   873.6  748.93     962  790.57   981.6  800.84   991.4  806.97
  1001.2  812.42  1011.1  817.04  1128.9  885.37  1168.1  908.94  1217.2  939.39
#Mann= 3 , 0 , 0
       0     .06       0   598.8    .045       0     697     .08       0
Bank Sta=598.8,697
XS Rating Curve= 0 ,0
Exp/Cntr=0.3,0.1

Type RM Length L Ch R = 1 ,22341   ,542.5,549,555.3
XS GIS Cut Line= 4
     1602394.182      333959.462     1602075.171      334363.108
     1601714.186      334878.308     1601711.022      335104.572
#Sta/Elev= 30
       0  815.98    38.8  812.71   184.4  798.03     233  794.75     330  785.64
   349.5  782.51   427.1  763.33   485.4  750.21   514.5  744.38   553.8  737.59
   701.2  714.19   730.7  711.78   789.7  708.45   808.8705.5379   819.2  704.34
   838.9     704   878.2  704.13     888  705.31   907.7  709.37  1064.9  719.92
  1074.8  722.08  1084.6  726.62  1143.6  761.91  1192.8  784.15    1242  808.73
  1261.6  816.99  1281.3  823.46    1301  827.93  1350.2  834.72  1369.8  836.28
#Mann= 3 , 0 , 0
       0     .06       0   808.8    .045       0     888      .1       0
Bank Sta=808.8,888
XS Rating Curve= 0 ,0
Exp/Cntr=0.3,0.1

Type RM Length L Ch R = 1 ,21792.1 ,824.5,813.3,802
XS GIS Cut Line= 4
     1601862.498      333651.302     1601728.164      334107.723
      1601291.12      334458.342     1601135.501      334892.622
#Sta/Elev= 30
       0  814.19    29.1  813.58   106.8   807.1     301  784.58   349.6  777.87
   407.8  764.69   446.6  754.13   515.1  733.87   564.2  716.26   662.6  714.92
   800.2  711.48   819.8  705.67   829.7  704.02   839.5     704   888.6  704.12
   898.5  705.46   918.1  710.15   957.4  713.28   967.3  715.04  1006.6  727.03
  1036.1  732.15  1075.3  743.79  1114.6  754.09  1163.7  770.59  1291.3  817.88
  1320.7  827.49  1350.2  835.76  1448.3  859.49  1477.8  863.36  1497.4  864.15
#Mann= 3 , 0 , 0
       0      .1       0   819.8    .045       0   898.5     .06       0
Bank Sta=819.8,898.5
XS Rating Curve= 0 ,0
Exp/Cntr=0.3,0.1

Type RM Length L Ch R = 1 ,20978.8 ,359.5,352.9,346.3
XS GIS Cut Line= 3
     1601056.514      333377.801     1600760.229       334082.85
     1600645.007       334333.87
#Sta/Elev= 30
       0  808.91      49  808.17      98  808.57   137.3  808.11   205.9  811.19
   215.7  811.04   225.5  808.75   235.3   803.6     304  754.79   323.6  741.69
   372.6  711.87   382.4  706.67   392.2  704.23   411.8     704     451     704
   460.8  704.52   480.4  709.04   490.2  709.69   568.7  708.69   617.7  710.14
   666.7   714.4   715.8  723.82   735.4  726.28   793.4  729.02   850.5  735.74
   898.1  739.42   926.7  740.75   974.3  740.68  1012.4  745.02    1041  746.65
#Mann= 3 , 0 , 0
       0      .1       0   392.2    .045       0   460.8     .06       0
Bank Sta=392.2,460.8
XS Rating Curve= 0 ,0
Exp/Cntr=0.3,0.1

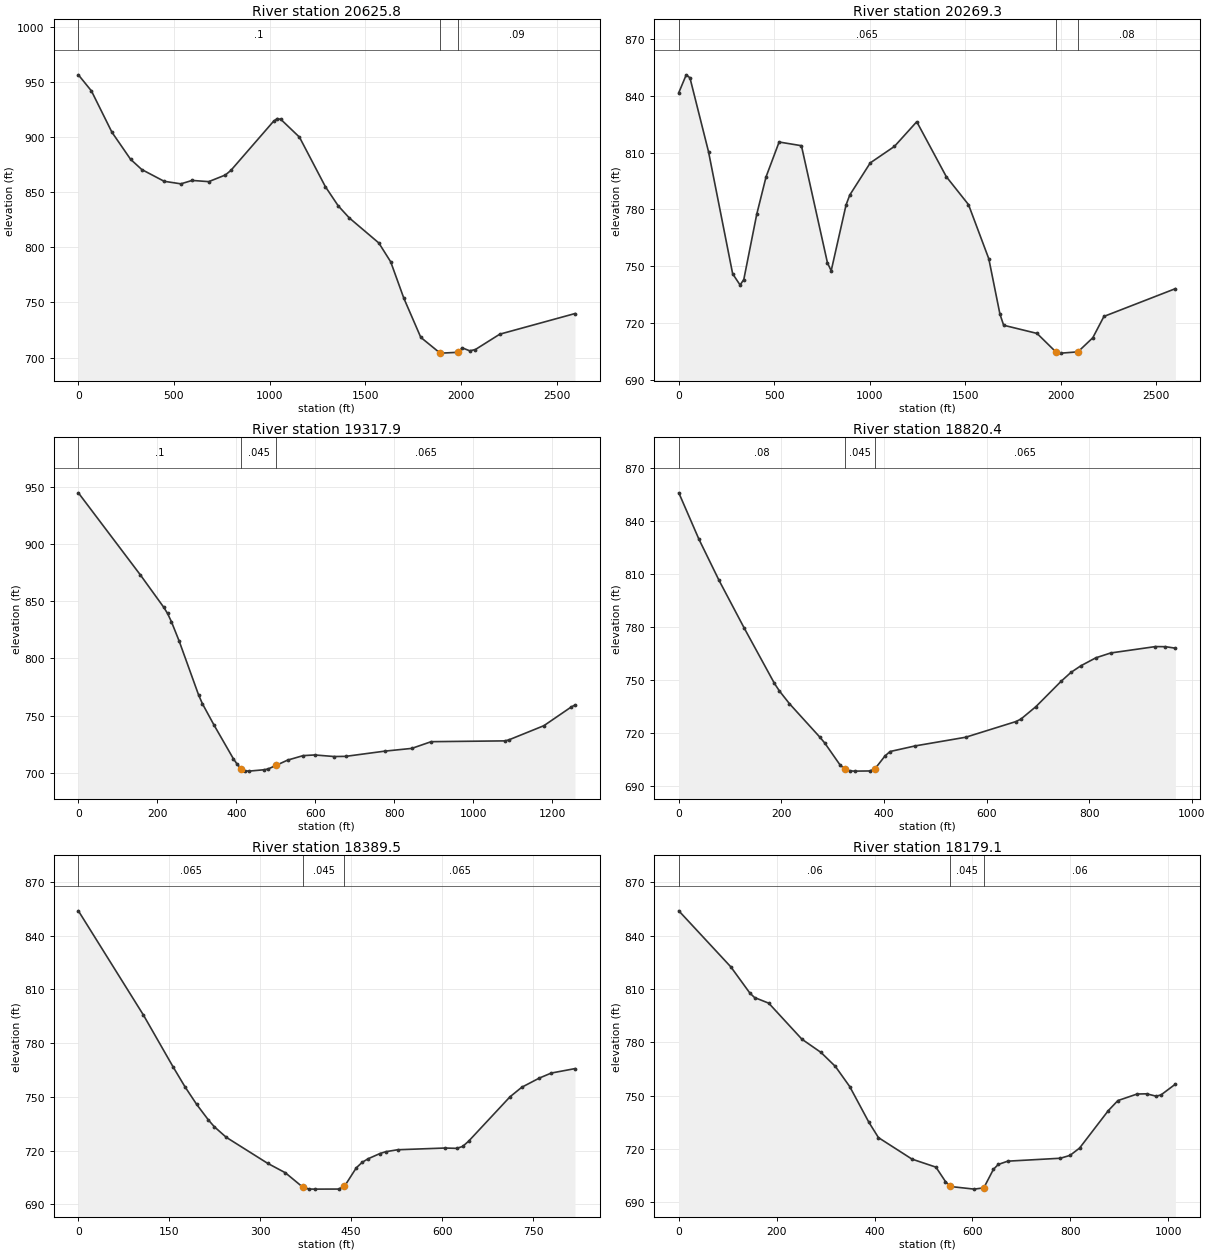
Type RM Length L Ch R = 1 ,20625.8 ,363.6,356.5,349.4
XS GIS Cut Line= 6
      1600542.66      331858.571     1600325.299      332432.877
     1600539.919      332951.545      1600578.41      333397.066
     1600526.042      333905.881     1600399.294      334349.982
#Sta/Elev= 30
       0  956.36    68.2  941.79   175.4  904.33   272.9  879.78   331.4   870.5
   448.4  859.83   536.1  857.51   594.6   860.6   681.8  859.51   768.9  865.56
   797.9  869.78  1020.5  914.24  1039.9  916.74  1059.2  915.88    1156  899.85
  1291.1  855.07  1358.7  837.55  1416.5  826.61  1570.9   803.9    1633  786.82
  1701.8  753.76  1790.4  718.29  1888.7  704.41  1898.6     704  1987.1  704.77
  2006.8  708.81  2046.1  706.11  2075.6  707.23  2203.4  721.18  2596.5  739.88
#Mann= 3 , 0 , 0
       0      .1       0  1888.7    .045       0  1987.1     .09       0
Bank Sta=1888.7,1987.1
XS Rating Curve= 0 ,0
Exp/Cntr=0.3,0.1

Type RM Length L Ch R = 1 ,20269.3 ,970.9,951.4,931.6
XS GIS Cut Line= 6
     1598788.055      332381.299     1599079.722      332745.883
      1599668.14      333257.155     1600043.264      333386.508
     1600142.222      333506.299     1600256.805      334297.966
#Sta/Elev= 30
       0  841.75    38.9  851.17    58.4  849.57   155.6  810.53   282.1  745.96
     321  740.02   340.4  742.92   408.5  777.56   457.2  797.27   525.4  815.64
   642.3  813.69   778.7  751.72   798.2  747.55   876.1  782.38   895.6  787.62
  1002.8   804.6  1129.5  813.32  1246.4  826.37  1401.2  797.31  1517.4  782.54
  1623.8  753.88    1682  724.67  1701.5  718.75  1876.4  714.42  1973.8  704.76
    2003     704  2090.6  704.67  2168.4  712.12  2226.8  723.41  2601.1  738.09
#Mann= 3 , 0 , 0
       0    .065       0  1973.8    .045       0  2090.6     .08       0
Bank Sta=1973.8,2090.6
XS Rating Curve= 0 ,0
Exp/Cntr=0.3,0.1

Type RM Length L Ch R = 1 ,19317.9 ,503.4,497.5,491.2
XS GIS Cut Line= 3
      1598991.18      333803.174      1599647.43      334157.341
     1600064.097      334454.216
#Sta/Elev= 30
       0  945.22     157  873.24   215.9     845   225.7  839.52   235.5  832.32
   255.1  815.36   304.2  768.21     314  760.37   343.4  741.65   392.5  712.07
   402.3  707.14   412.1  703.51   421.9  701.58   431.7  701.24     471  702.47
   480.8  703.21   500.4  706.24   529.8   710.9   569.1  714.84   598.5  715.42
   647.6  714.04     677  714.19   775.2  718.74   844.1  721.17   893.3  727.06
  1080.2  727.76  1090.1  728.67  1178.6  741.07  1247.5  757.38  1257.3  759.22
#Mann= 3 , 0 , 0
       0      .1       0   412.1    .045       0   500.4    .065       0
Bank Sta=412.1,500.4
XS Rating Curve= 0 ,0
Exp/Cntr=0.3,0.1

Type RM Length L Ch R = 1 ,18820.4 ,430,430.9,431.5
XS GIS Cut Line= 3
     1598831.412      334384.183     1599539.745      334543.038
     1599753.287      334657.621
#Sta/Elev= 30
       0  855.85    39.2  829.65    78.5  806.33   127.5  779.41   186.4  748.14
   196.2  743.82   215.8  736.62   274.7  717.82   284.5  714.43   313.9  702.21
   323.7  699.56   333.5  698.63   343.3   698.5   372.8   698.6   382.6  699.85
   402.2  707.13     412  709.59   461.1  712.77   559.2  717.65   657.3  726.52
   667.1  727.93   696.5  735.01   745.3  749.25   764.7  754.32   784.1  758.08
   813.2  762.57   842.2  765.31   929.5  768.92   948.9  768.86   968.3  768.01
#Mann= 3 , 0 , 0
       0     .08       0   323.7    .045       0   382.6    .065       0
Bank Sta=323.7,382.6
XS Rating Curve= 0 ,0
Exp/Cntr=0.3,0.1

Type RM Length L Ch R = 1 ,18389.5 ,215.7,210.4,205.6
XS GIS Cut Line= 3
     1598704.582      334775.989     1599099.722      334884.003
     1599497.127      334982.691
#Sta/Elev= 30
       0  853.78   107.3  795.64     156  766.85   175.6  755.74   195.1  745.79
   214.6  737.04   224.3  733.29   243.8  727.45   312.1  712.92   341.4  707.63
   370.6  699.48   380.4  698.55   390.1   698.5   429.1  698.54   438.9  700.05
   458.4  710.38   468.1  713.45   477.9  715.44   497.4  718.35   507.1  719.38
   526.6  720.47   604.6  721.43   624.1  721.25   633.9  722.33   643.6  725.22
   711.9     750   731.4  755.35   760.6  760.51   780.1  763.27   819.1  765.74
#Mann= 3 , 0 , 0
       0    .065       0   370.6    .045       0   438.9    .065       0
Bank Sta=370.6,438.9
XS Rating Curve= 0 ,0
Exp/Cntr=0.3,0.1

Type RM Length L Ch R = 1 ,18179.1 ,70.7,70.6,70.5
XS GIS Cut Line= 3
     1598515.306      334889.385     1598700.028      335074.107
     1599453.197      335097.021
#Sta/Elev= 30
       0  853.96   106.4  822.41   145.1  807.74   154.8  805.18   183.8  802.01
   251.6  781.74   290.6  774.29     320  766.41   349.3  755.09   388.4  735.02
     408  726.38   476.5  714.29   525.5  709.76     545  701.64   554.8  698.88
   603.7   697.4   623.3  698.13   642.9  708.51   652.7  711.26   672.2  713.13
   779.9  714.78   799.5  716.39     819   720.5   877.8   741.6   897.3  747.22
   936.5   750.9     956  751.02   975.6  749.68   985.4   750.4  1014.8  756.46
#Mann= 3 , 0 , 0
       0     .06       0   554.8    .045       0   623.3     .06       0
Bank Sta=554.8,623.3
XS Rating Curve= 0 ,0
Exp/Cntr=0.3,0.1

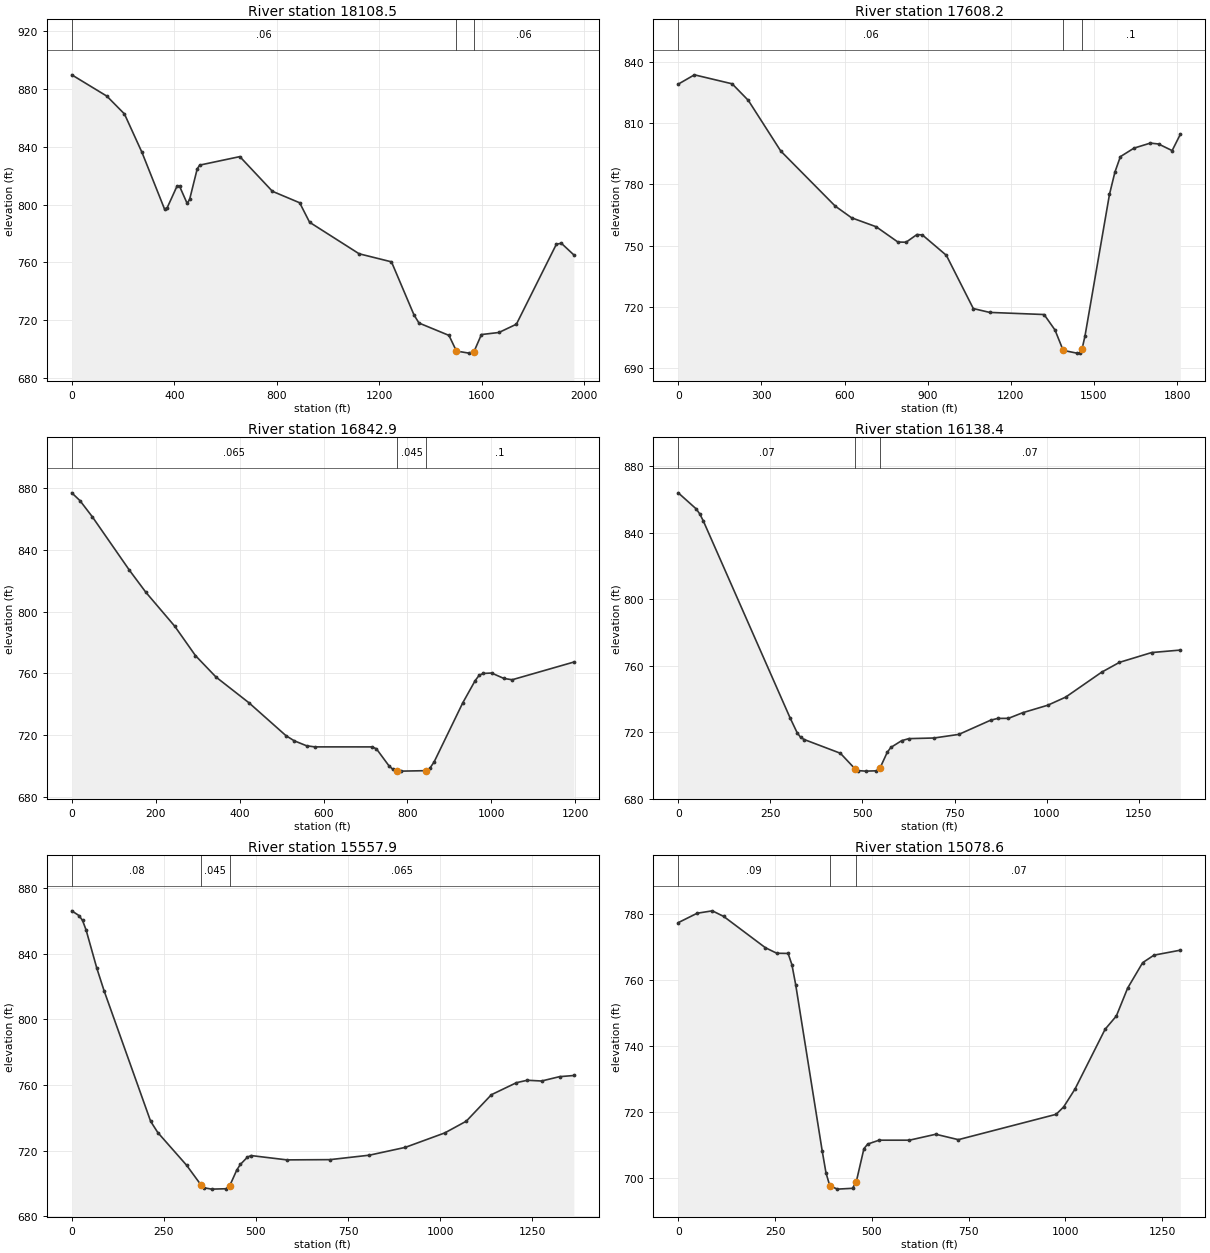
Type RM Length L Ch R = 1 ,18108.5 ,494.2,500.3,506.2
XS GIS Cut Line= 4
     1597612.436      334645.867     1598281.001      335034.582
     1598681.973      335144.941     1599451.885      335166.159
#Sta/Elev= 30
       0  889.56     137  874.84   205.6  862.54   274.1  835.96   362.2  796.79
     372  797.64   411.2  812.86   420.9  812.53   450.3  800.74   460.1  803.64
   489.5   824.6   499.3  827.22   655.9  833.09     783  809.14   889.4  801.21
   928.1  787.77  1121.5  765.99  1247.7  760.43  1335.5  723.82    1355  718.18
    1472  709.65  1501.2  698.82    1550   697.4  1569.5  698.36  1598.7  710.23
    1667  711.65  1735.2  717.37  1891.2   772.6  1910.7  773.25  1959.4  765.21
#Mann= 3 , 0 , 0
       0     .06       0  1501.2    .045       0  1569.5     .06       0
Bank Sta=1501.2,1569.5
XS Rating Curve= 0 ,0
Exp/Cntr=0.3,0.1

Type RM Length L Ch R = 1 ,17608.2 ,766.3,765.3,764.3
XS GIS Cut Line= 5
     1597820.769      336031.978     1598061.527      335791.158
     1598550.702       335560.92     1598677.806      335517.163
     1599440.306       335746.33
#Sta/Elev= 30
       0  828.96    58.4  833.52   194.6  829.12     253     821     370  796.24
   566.6   769.3   625.6  763.59   714.1  759.22   792.7  751.74   822.2  751.65
   861.5  755.41   881.2  755.19   967.6  745.23  1064.8   719.2  1123.7  717.32
  1320.3  716.28  1359.6  708.71  1389.1  698.74  1438.3   697.4  1448.1   697.5
  1457.5699.5623  1467.8  705.76  1556.2  775.05  1575.9  785.98  1595.5   793.5
  1644.7  797.67  1703.7  800.13  1733.2  799.69  1782.3  796.46  1811.8  804.41
#Mann= 3 , 0 , 0
       0     .06       0  1389.1    .045       0  1457.5      .1       0
Bank Sta=1389.1,1457.5
XS Rating Curve= 0 ,0
Exp/Cntr=0.3,0.1

Type RM Length L Ch R = 1 ,16842.9 ,714.1,704.5,695
XS GIS Cut Line= 3
     1598023.961      336347.282     1598469.154      336270.079
     1599191.488      336452.059
#Sta/Elev= 30
       0   876.8    19.6  871.73    49.1  861.26   137.5  826.68   176.8  812.37
   245.6  790.42   294.7   771.5   343.8  757.58   422.4  740.91   510.6  719.64
   530.2  716.34   559.6  713.11   579.3  712.39   716.5  712.38   726.3  711.08
   755.7  700.26   765.5  697.82   775.3  696.86   785.1   696.7   843.9     697
   853.7  698.67   863.5  702.57   932.1  740.98   961.5  755.28   971.3   758.8
   981.1  759.93  1000.7  760.18  1030.1  756.66  1049.7  755.84  1196.7  767.29
#Mann= 3 , 0 , 0
       0    .065       0   775.3    .045       0   843.9      .1       0
Bank Sta=775.3,843.9
XS Rating Curve= 0 ,0
Exp/Cntr=0.3,0.1

Type RM Length L Ch R = 1 ,16138.4 ,604.1,580.5,556.5
XS GIS Cut Line= 4
     1598176.044       337143.05     1598859.638      337021.957
     1599021.709      336901.874     1599239.998      336489.643
#Sta/Elev= 30
       0  863.94    48.9  854.26    58.7  851.15    68.4  846.88   303.1  728.91
   322.7  719.76   332.4  716.91   342.2  715.66     440  707.44   479.1  698.23
   488.9  697.01   508.4   696.7   537.8  696.89   547.6   698.6   567.1  707.98
   576.9  710.93   606.2     715   625.8  716.23   694.2  716.61   761.5  718.78
   847.9  727.32   867.1  728.38     896  728.42   934.8  731.81  1002.8  736.31
  1051.4  741.18  1148.6  756.11  1197.2  762.06  1284.7  767.96  1362.4  769.45
#Mann= 3 , 0 , 0
       0     .07       0   479.1    .045       0   547.6     .07       0
Bank Sta=479.1,547.6
XS Rating Curve= 0 ,0
Exp/Cntr=0.3,0.1

Type RM Length L Ch R = 1 ,15557.9 ,488.9,479.3,469.7
XS GIS Cut Line= 3
     1598914.846      337783.068     1599091.929      337277.859
       1599323.7      336483.589
#Sta/Elev= 30
       0  866.04    19.5  863.17    29.2  860.21    38.9  854.36    68.1  831.02
    87.6  817.44   214.1  737.89   233.6  731.04   311.5  711.21   350.4  699.28
   360.1   697.4   379.6  696.63   418.5  696.86   428.3  698.47   447.7  708.17
   457.5  711.66   476.9  716.12   486.7  717.06     584  714.43   700.8  714.58
   807.9   717.3   905.2  722.05  1012.3  730.84  1070.7  737.98  1138.9   754.1
    1207  761.43  1236.2   762.9  1275.1  762.45  1323.8  765.09  1362.7   765.8
#Mann= 3 , 0 , 0
       0     .08       0   350.4    .045       0   428.3    .065       0
Bank Sta=350.4,428.3
XS Rating Curve= 0 ,0
Exp/Cntr=0.3,0.1

Type RM Length L Ch R = 1 ,15078.6 ,351.2,349.8,348.1
XS GIS Cut Line= 3
     1599549.889      337896.058     1599495.522      337291.642
     1599646.096      336618.311
#Sta/Elev= 30
       0  777.47    48.9  780.33    88.1  781.06   117.5  779.35   225.1  769.87
   254.5  768.19   283.8  768.13   293.6  764.72   303.4  758.63   371.9  708.17
   381.7  701.51   391.5  697.63   411.1  696.62   450.2  696.87     460  698.93
   479.6   708.9   489.4  710.29   518.8  711.47   597.1  711.47   665.2  713.27
   723.5  711.63   976.1  719.32   995.6  721.58  1024.7  726.97  1102.5  745.12
  1131.6  749.15  1160.8  757.62  1199.6  765.34  1228.8  767.61  1296.8  769.12
#Mann= 3 , 0 , 0
       0     .09       0   391.5    .045       0     460     .07       0
Bank Sta=391.5,460
XS Rating Curve= 0 ,0
Exp/Cntr=0.3,0.1

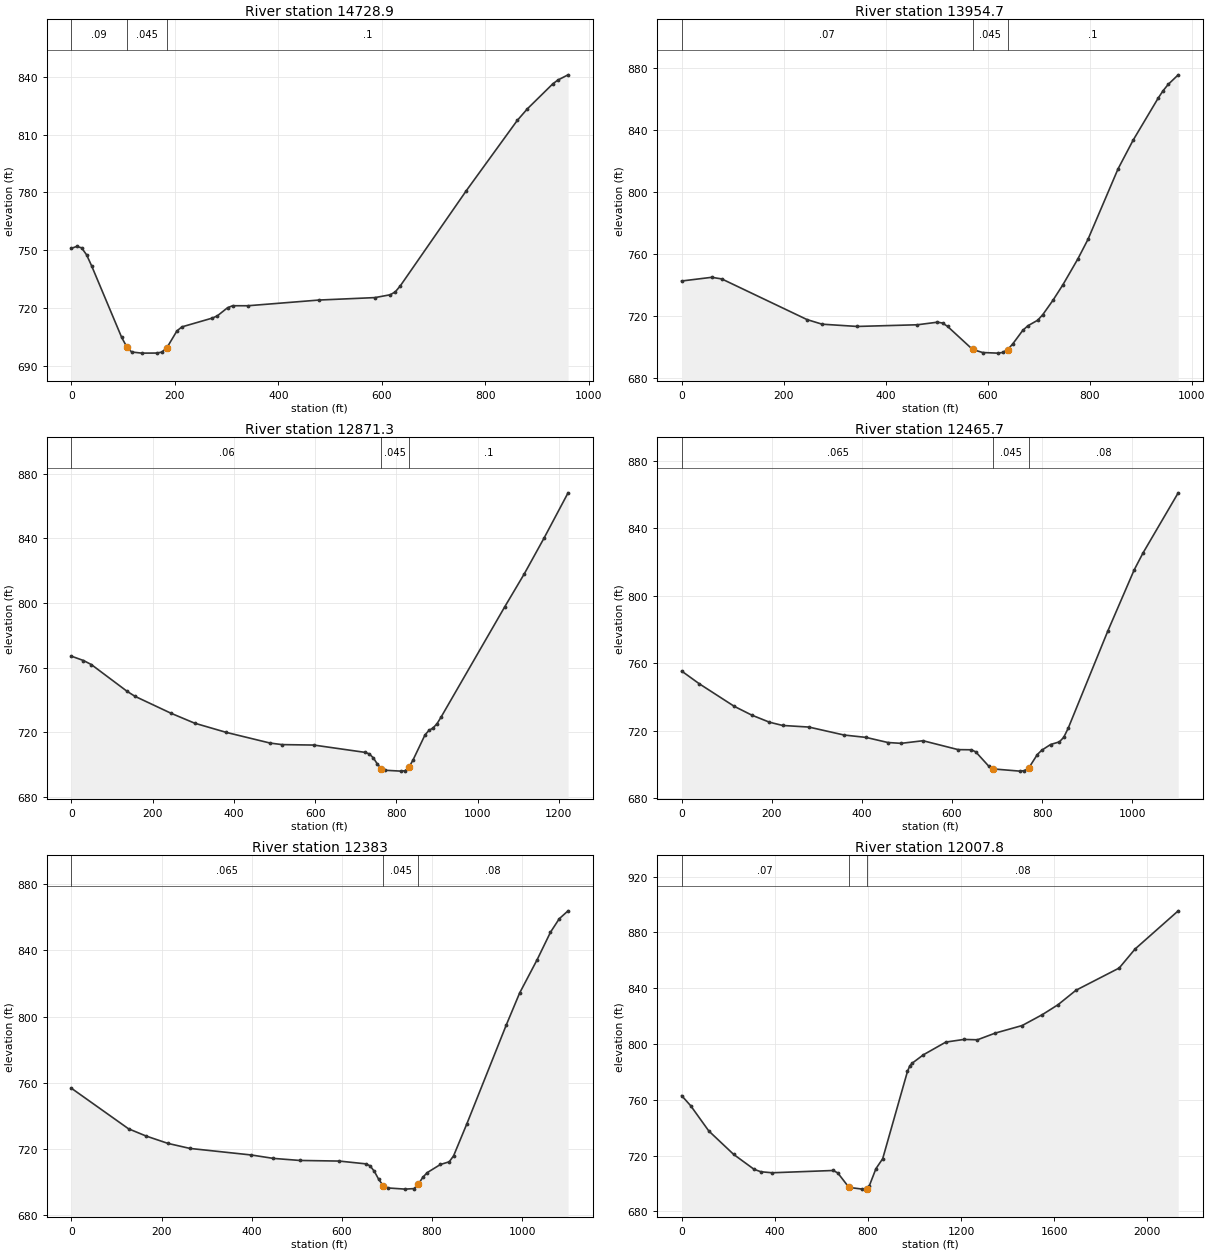
Type RM Length L Ch R = 1 ,14728.9 ,740.4,774.1,807.8
XS GIS Cut Line= 3
     1599876.825      337551.167     1599839.856      337321.267
     1600052.346      336626.123
#Sta/Elev= 30
       0  750.99     9.7  751.95    19.4  751.28    29.1  747.66    38.8  741.97
      97  704.75   107.5699.5289   116.4  697.18   135.8   696.6   164.9  696.64
   174.6  697.13   184.3  699.36   203.8  708.14   213.4  710.22   272.2  714.79
     282  715.97   301.6  720.15   311.4   721.2   340.9  721.19   478.4  724.15
   586.5  725.42     616  726.89   625.8  728.39   635.6  731.54   763.3  780.98
   861.5  817.34   881.2  823.41   930.3  836.36   940.1  838.33   959.8  841.04
#Mann= 3 , 0 , 0
       0     .09       0   107.5    .045       0   184.3      .1       0
Bank Sta=107.5,184.3
XS Rating Curve= 0 ,0
Exp/Cntr=0.3,0.1

Type RM Length L Ch R = 1 ,13954.7 ,1068.9,1083.4,1097.8
XS GIS Cut Line= 2
      1599942.06      337650.863      1600888.24      337420.828
#Sta/Elev= 30
       0   742.5      59  744.88    78.7  743.83   245.9  717.62   275.4  714.66
   344.2   713.2   462.3  714.28   501.6  715.95   511.5   715.4   521.3  713.27
   570.5  698.37   590.2  696.39   619.6     696   629.5  696.41   639.3   698.3
   649.2  701.92   668.8  710.63   678.7  713.59   698.3  717.25   708.2  720.85
   727.8  729.93   747.5  740.03     777   756.8   796.7  769.31   855.7  814.78
   885.2  833.24   934.4  860.41   944.2  865.25   954.1  869.27   973.7  875.42
#Mann= 3 , 0 , 0
       0     .07       0   570.5    .045       0   639.3      .1       0
Bank Sta=570.5,639.3
XS Rating Curve= 0 ,0
Exp/Cntr=0.3,0.1

Type RM Length L Ch R = 1 ,12871.3 ,405,405.6,406
XS GIS Cut Line= 2
     1599622.478      338247.943     1600747.478       338727.11
#Sta/Elev= 30
       0  767.06    29.4   764.4    48.9  761.89     137  745.33   156.5  742.24
   244.6  731.84   303.2  725.65   381.5  719.93   489.1  713.35   518.5   712.4
   596.7  712.12   723.9  707.56   733.7   706.6   743.5  704.11   753.2  700.38
     763  697.56   772.8  696.53   811.1     696   821.7  696.26   831.5  698.58
   841.3  703.05   870.6  718.45   880.4  721.23   890.2  722.65     900   725.3
   909.8  729.29  1066.3  797.37  1115.2  818.08  1164.1  840.32  1222.8  868.08
#Mann= 3 , 0 , 0
       0     .06       0     763    .045       0   831.5      .1       0
Bank Sta=763,831.5
XS Rating Curve= 0 ,0
Exp/Cntr=0.3,0.1

Type RM Length L Ch R = 1 ,12465.7 ,82.8,82.7,82.8
XS GIS Cut Line= 3
     1599483.589      338610.703     1600052.166      338865.912
     1600488.366      339062.714
#Sta/Elev= 30
       0  755.33      39   747.8   116.8  734.38   155.8  729.15   194.8  724.97
     224  723.04   282.4  722.08   360.3  717.36     409  715.95   457.7  712.91
   486.9  712.42   535.6  713.97   613.5  708.69   642.8   708.6   652.5  707.38
   681.8  698.76   691.6  697.23   750.2  695.93     760  696.18   769.7   697.6
   789.2  705.78     799  708.34   818.6  711.73   838.1  713.29   847.8     716
   857.6  721.34   945.5  779.03  1004.1  815.36  1023.6  825.37  1101.8   861.1
#Mann= 3 , 0 , 0
       0    .065       0   691.6    .045       0   769.7     .08       0
Bank Sta=691.6,769.7
XS Rating Curve= 0 ,0
Exp/Cntr=0.3,0.1

Type RM Length L Ch R = 1 ,12383   ,365.9,375.1,384.5
XS GIS Cut Line= 3
     1599450.603      338686.224      1600019.18      338941.432
      1600455.38      339138.235
#Sta/Elev= 30
       0  756.75   126.6  732.31   165.5  727.95   214.2  723.48   262.9  720.46
   399.2   716.5   447.9  714.45   506.4  713.21     594  712.84   652.5  711.17
   662.3  710.01   672.1  706.57   681.8  701.72   691.6  698.04   701.4  696.62
   740.4   695.9     760  696.22   769.7  698.96   779.5  703.02   789.2  705.85
   818.6  710.78   838.1  712.39   847.8     716   877.2   735.3     965  795.18
   994.3  814.25  1033.4  834.49  1062.7  850.92  1082.2  859.09  1101.8  863.87
#Mann= 3 , 0 , 0
       0    .065       0   691.6    .045       0   769.7     .08       0
Bank Sta=691.6,769.7
XS Rating Curve= 0 ,0
Exp/Cntr=0.3,0.1

Type RM Length L Ch R = 1 ,12007.8 ,951.1,940.4,929.8
XS GIS Cut Line= 6
     1599347.478      338810.443     1599830.811       339202.11
     1600012.057      339402.511     1600360.462      339549.228
     1600725.046      339562.249     1601215.497      339479.784
#Sta/Elev= 30
       0  762.93    38.9  755.68   116.6   737.6   223.6  720.76     311  710.12
   340.2  708.36   388.8  707.63     651  709.27   670.4  707.52   718.6  697.14
   776.5   695.9   795.8  696.08   805.5  698.09   834.4  710.58   863.4  717.72
   969.9  780.36   979.6   784.2   989.2  786.09  1037.7  792.16  1134.6  801.33
  1212.2  803.22  1270.4  802.98  1347.2  807.79  1462.4  813.19  1548.8  820.99
    1616  828.07  1693.7  838.51    1879  854.42  1947.2  868.05  2132.5  895.43
#Mann= 3 , 0 , 0
       0     .07       0   718.6    .045       0   795.8     .08       0
Bank Sta=718.6,795.8
XS Rating Curve= 0 ,0
Exp/Cntr=0.3,0.1