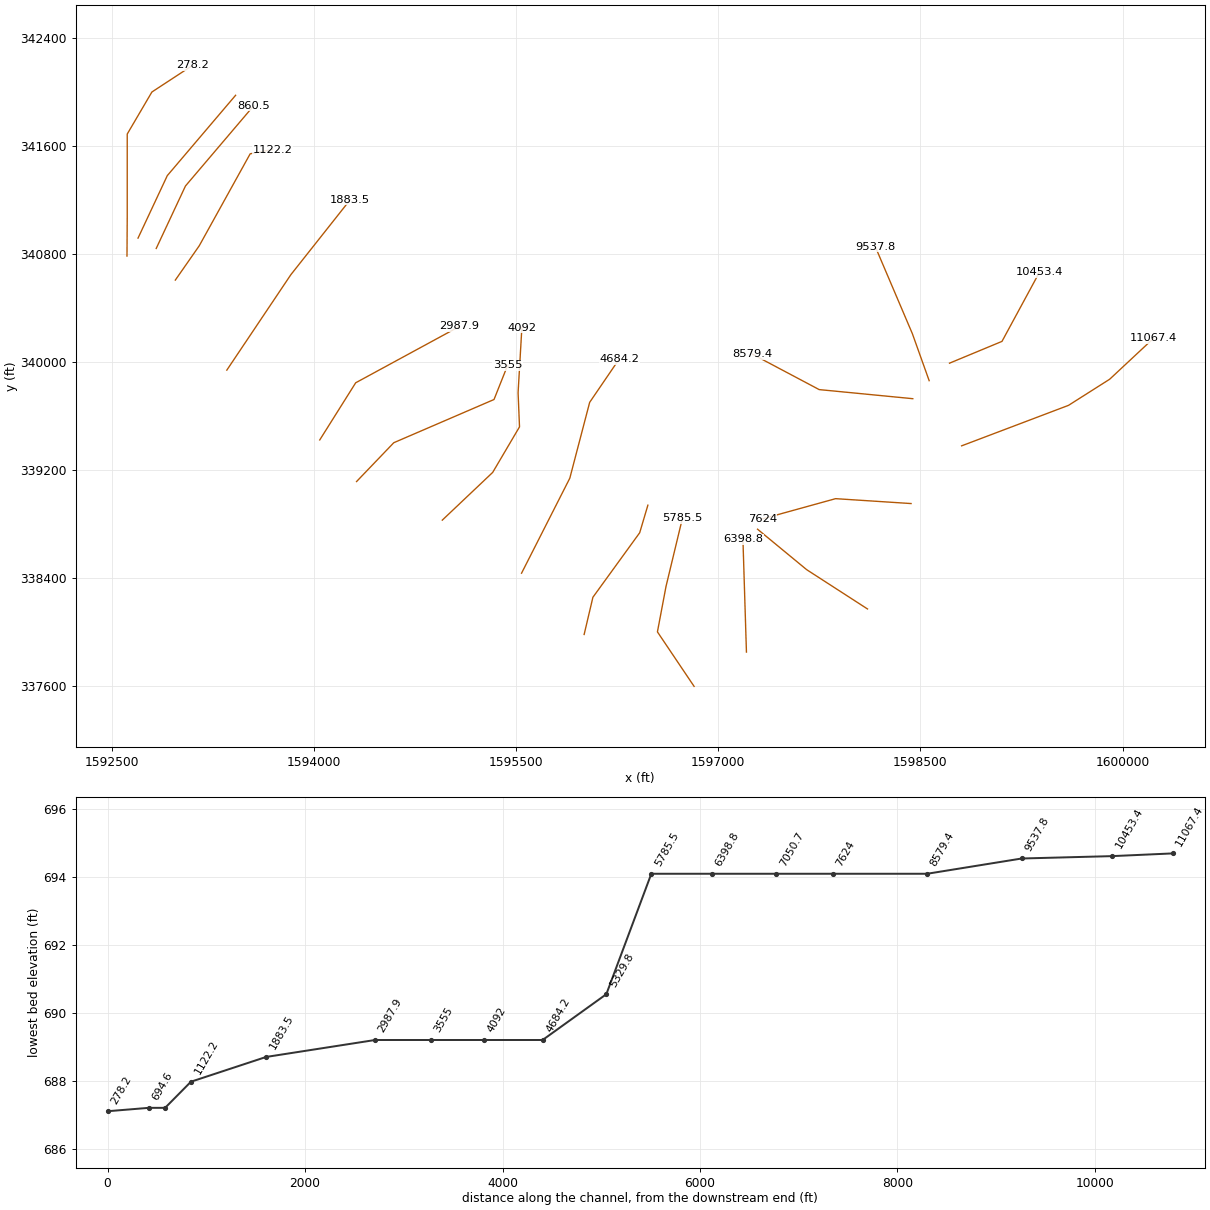
HEC-RAS study MCLRYCRK.prj: MCLRYCRK

--- MCLRYCRK.g01 (geometry) --- (continued)

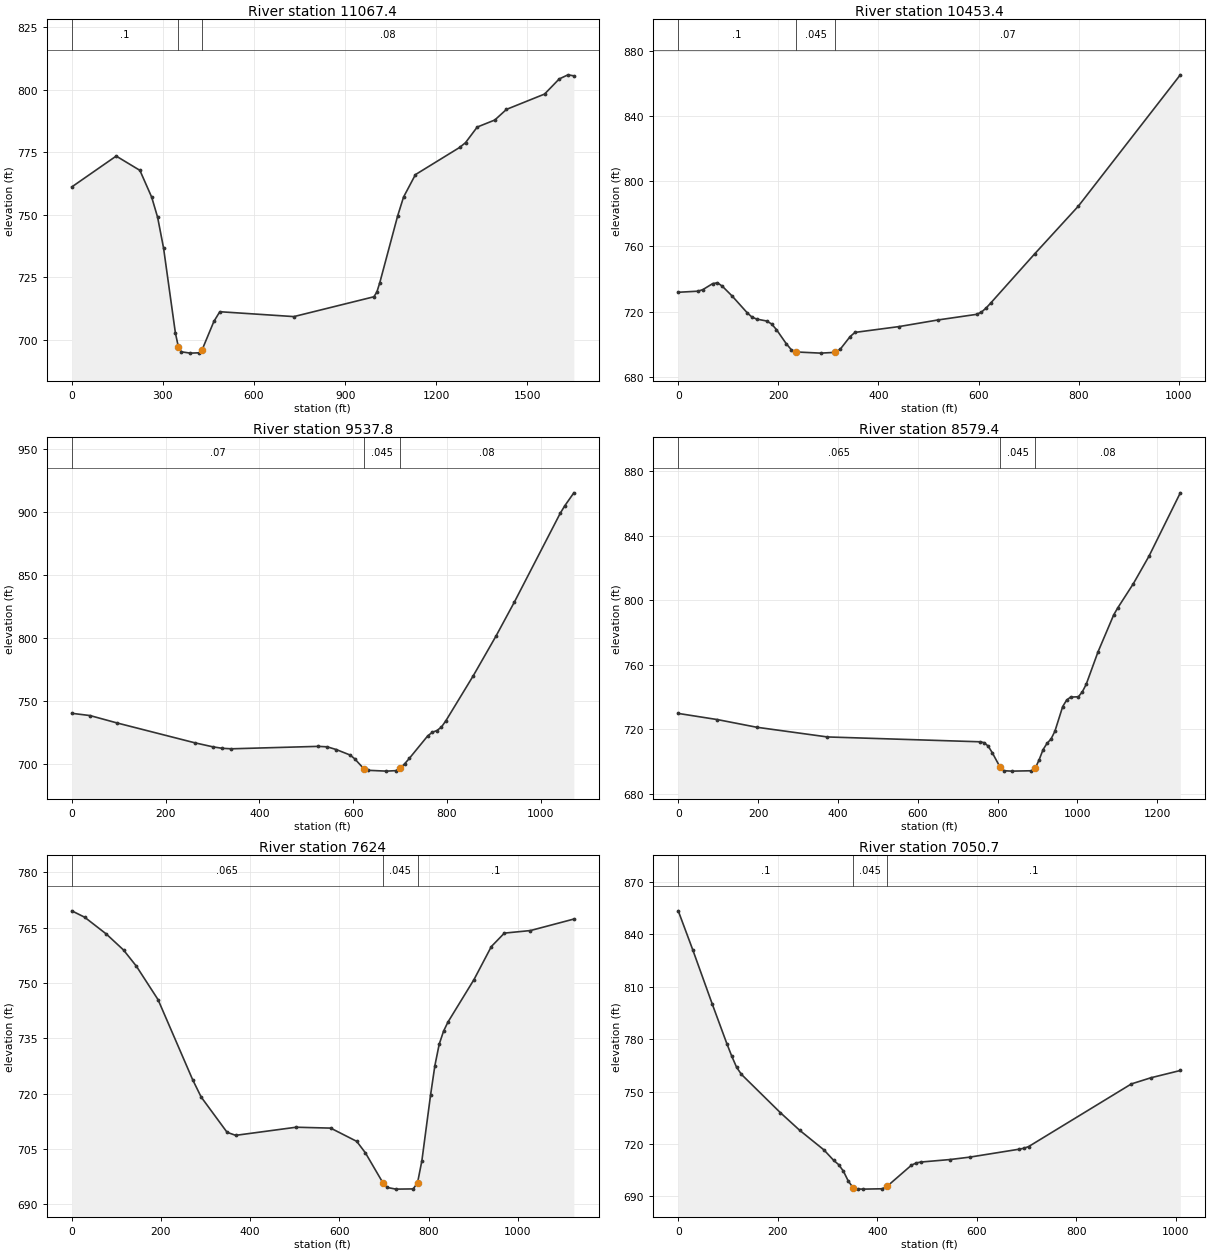
Type RM Length L Ch R = 1 ,11067.4 ,613.1,614,614.5
XS GIS Cut Line= 4
     1598806.184      339380.589     1599599.356      339680.271
     1599904.696        339873.5     1600229.227      340175.555
#Sta/Elev= 30
       0  761.12   146.2  773.46   224.2  767.75   263.1  757.02   282.6  748.97
   302.1  736.72   341.1  702.75   350.8  697.26   360.6  695.23   389.8   694.7
   419.1  694.83   428.8  695.97   467.8  707.38   487.3  711.25     731   709.3
   994.4  717.22  1004.2  719.11  1013.9  722.87  1072.5  749.48    1092  757.06
  1131.1  766.04  1276.7  776.91    1296  778.81  1334.5  785.05  1392.4  787.87
  1430.9  792.12  1556.2  798.24  1604.4  804.28  1633.3  805.93  1652.6  805.52
#Mann= 3 , 0 , 0
       0      .1       0   350.8    .045       0   428.8     .08       0
Bank Sta=350.8,428.8
XS Rating Curve= 0 ,0
Exp/Cntr=0.3,0.1

Type RM Length L Ch R = 1 ,10453.4 ,879.9,915.6,951.3
XS GIS Cut Line= 3
     1598716.129      339992.284     1599105.646      340153.654
     1599383.065      340664.427
#Sta/Elev= 30
       0  731.92    39.2  732.59      49  733.51    68.6   737.2    78.4  737.76
    88.2  735.59   107.9  729.55   137.3  719.51   147.1  716.73   156.9  715.47
   176.5  714.32   186.3  712.54   196.1  709.08   215.7  700.44   225.5  696.84
   235.3  695.34   284.4  694.62   313.8  695.09   323.6  697.02   343.2  704.72
     353  707.32     441  710.89   518.5  714.94     596  718.39   605.7  719.76
   615.4   722.4   625.1  725.63   712.2  755.54   799.4  784.78  1002.9  865.21
#Mann= 3 , 0 , 0
       0      .1       0   235.3    .045       0   313.8     .07       0
Bank Sta=235.3,313.8
XS Rating Curve= 0 ,0
Exp/Cntr=0.3,0.1

Type RM Length L Ch R = 1 ,9537.8  ,942.9,958.3,973.6
XS GIS Cut Line= 3
     1598565.156      339863.007     1598440.534      340210.719
     1598165.134       340855.37
#Sta/Elev= 30
       0  740.34    38.9  738.55    97.2  732.63   262.4  716.97   301.3  713.75
   320.8  712.63   340.2  712.23   525.2  714.16   544.6   713.8   564.1  711.61
   593.3  707.31     603  704.37   622.5  696.54   632.2  695.19   670.8  694.55
   690.7  694.92   700.4  696.95   710.1  700.53   719.9  704.75   758.8  722.42
   768.6  725.32   778.3  726.64     788   729.4   797.8  734.57   856.2  770.22
   904.9  801.81   943.8  828.56  1041.2  898.61  1050.9  904.57  1070.4  914.92
#Mann= 3 , 0 , 0
       0     .07       0   622.5    .045       0   700.4     .08       0
Bank Sta=622.5,700.4
XS Rating Curve= 0 ,0
Exp/Cntr=0.3,0.1

Type RM Length L Ch R = 1 ,8579.4  ,938.3,955.4,972.3
XS GIS Cut Line= 3
     1598443.914      339729.511     1597749.143      339796.796
     1597254.338      340058.376
#Sta/Elev= 30
       0  729.85    98.3  726.03   196.6  721.29   373.6  715.28   756.9  712.27
   766.8  711.67   776.6  709.53   786.4  705.63     806  696.67   815.8  694.35
   835.5   694.1   884.6  694.33   894.4  695.97   904.2  701.21     914  707.47
   923.9  711.34   933.7  713.95   943.5  718.78   963.1  734.13     973  738.13
   982.8  739.96  1002.4  740.18  1012.2  743.22    1022  747.92  1051.5  767.97
  1090.8  790.88  1100.6   795.1  1139.9  810.19  1179.2  827.28  1257.7  866.54
#Mann= 3 , 0 , 0
       0    .065       0     806    .045       0   894.4     .08       0
Bank Sta=806,894.4
XS Rating Curve= 0 ,0
Exp/Cntr=0.3,0.1

Type RM Length L Ch R = 1 ,7624    ,592.4,573.4,554.3
XS GIS Cut Line= 3
     1598430.893       338953.47     1597870.917      338989.656
     1597326.458      338839.584
#Sta/Elev= 30
       0  769.54      29   767.8    77.4  763.26   116.1  758.92   145.1   754.5
   193.5  745.46   270.9  723.81   290.2  719.06   348.3   709.5   367.6  708.68
   503.1  710.88   580.6  710.64     639  707.05   658.5  703.93   697.5  695.86
   707.2  694.56   726.7   694.1   765.6  694.16   775.4  695.82   785.1  701.79
   804.6  719.61   814.3   727.6     824   733.4   833.8  736.94   843.5  739.37
     902  750.91   940.9  759.86   970.1   763.5  1028.5  764.19  1125.9  767.31
#Mann= 3 , 0 , 0
       0    .065       0   697.5    .045       0   775.4      .1       0
Bank Sta=697.5,775.4
XS Rating Curve= 0 ,0
Exp/Cntr=0.3,0.1

Type RM Length L Ch R = 1 ,7050.7  ,673.6,651.9,629.9
XS GIS Cut Line= 3
     1598107.701      338173.306     1597656.312      338464.104
     1597291.728      338763.583
#Sta/Elev= 30
       0  853.55    29.3  831.12    68.3  800.18    97.6  777.52   107.4  770.38
   117.2  763.95   126.9  759.87     205  737.97   244.1  727.79   292.9  716.54
   312.4  710.55   322.2  708.18   331.9  704.39   341.7   698.7   351.5  694.86
   361.2  694.18     371   694.1     410   694.3     420695.7961   468.6  707.82
   478.4  709.13   488.1  709.63   546.8  711.07   586.1  712.45   684.4  716.95
   694.2   717.5     704  718.48   910.5  754.38   949.8  757.91  1008.8  762.07
#Mann= 3 , 0 , 0
       0      .1       0   351.5    .045       0     420      .1       0
Bank Sta=351.5,420
XS Rating Curve= 0 ,0
Exp/Cntr=0.3,0.1

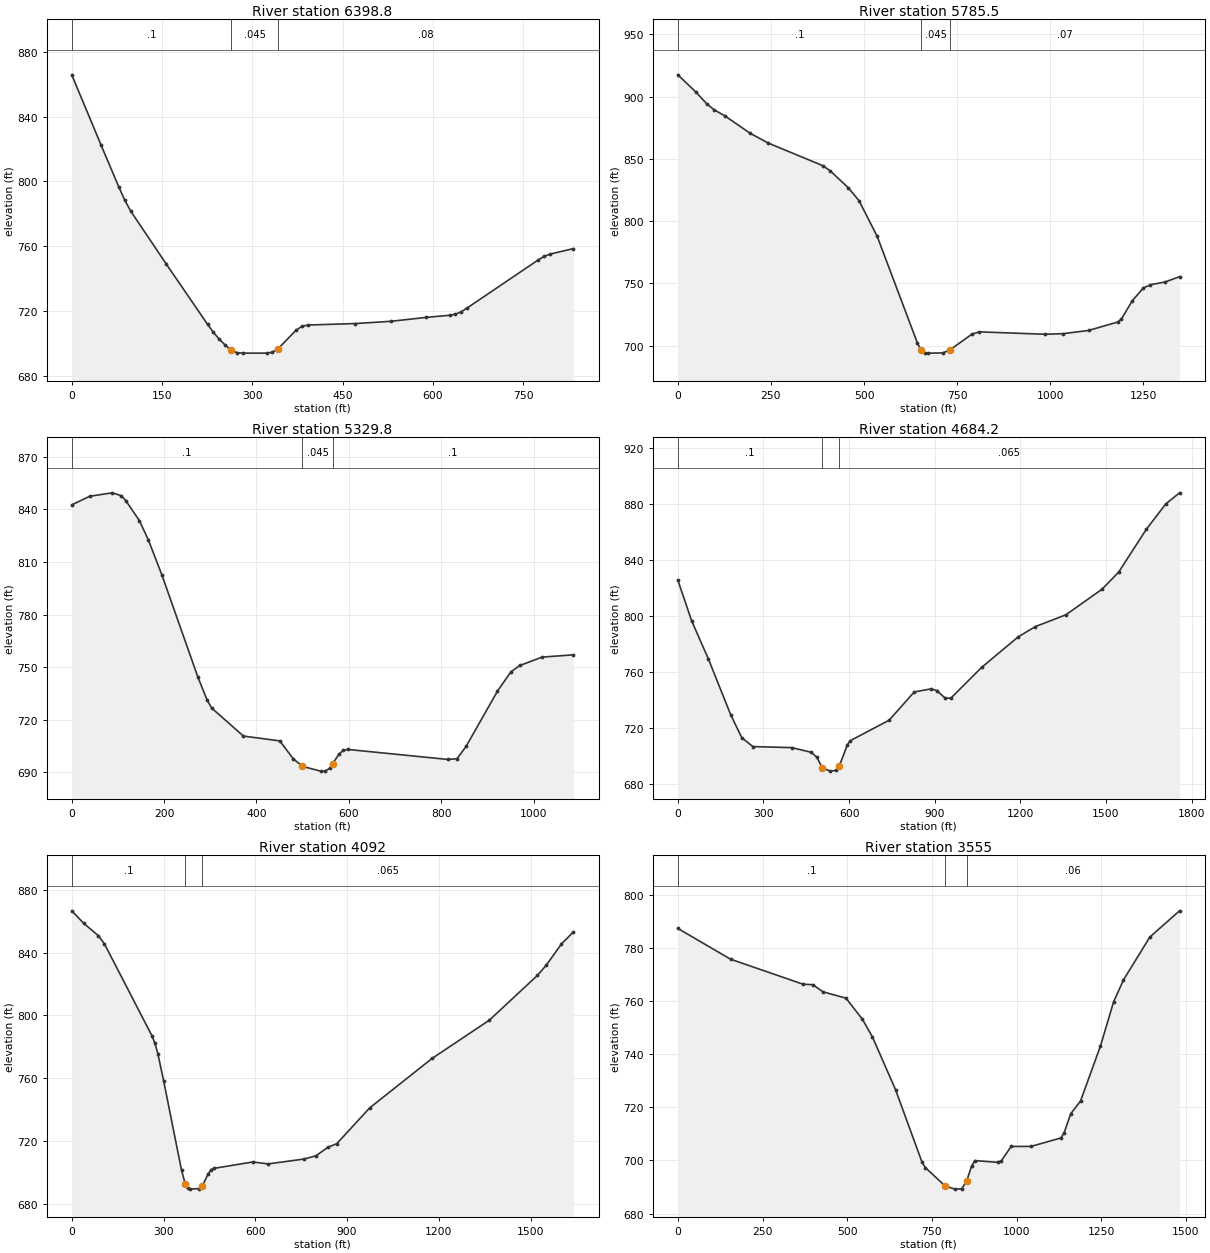
Type RM Length L Ch R = 1 ,6398.8  ,618.1,613.3,608.3
XS GIS Cut Line= 2
     1597209.263      337854.295     1597183.222      338687.629
#Sta/Elev= 30
       0  865.81      49  822.22    78.5  796.36    88.3  788.34    98.1  781.66
   156.9  749.17   225.6  711.91   235.4   706.9   245.2  702.68     255  699.07
   264.8  695.92   274.6  694.37   284.4   694.1   323.7   694.1   333.5  694.64
   342.8696.7941   372.7  708.25   382.5  710.63   392.4  711.43   470.8  712.35
   529.7  713.71   588.5  716.13   627.8  717.45   637.6  718.09   647.4  719.66
   657.2  721.99   774.9  751.55   784.7  753.72   794.5  755.17   833.7   758.6
#Mann= 3 , 0 , 0
       0      .1       0   264.8    .045       0   342.8     .08       0
Bank Sta=264.8,342.8
XS Rating Curve= 0 ,0
Exp/Cntr=0.3,0.1

Type RM Length L Ch R = 1 ,5785.5  ,465.6,455.7,445.7
XS GIS Cut Line= 4
     1596820.808      337600.389     1596548.694      338003.784
     1596612.475      338340.406     1596734.003      338843.879
#Sta/Elev= 30
       0  917.46    48.7  903.61    77.9  894.15    97.3  889.45   126.5  884.49
   194.6  870.46   243.3  862.62   389.3  844.56   408.7  840.53   457.4  826.92
   486.6  816.42   535.5  787.72   643.2   702.3     653  696.42   662.8   694.3
   672.6   694.1   711.7  694.25   731.3  696.84     790  709.37   809.6  711.18
   985.6  709.25  1034.4  709.71  1102.8   712.3    1181  719.03  1190.8  721.39
  1220.1  736.04  1249.4  746.26    1269  749.01    1308  751.15  1347.1  755.48
#Mann= 3 , 0 , 0
       0      .1       0     653    .045       0   731.3     .07       0
Bank Sta=653,731.3
XS Rating Curve= 0 ,0
Exp/Cntr=0.3,0.1

Type RM Length L Ch R = 1 ,5329.8  ,642,645.5,649.1
XS GIS Cut Line= 4
     1596004.836      337984.504      1596069.94      338260.111
     1596417.163      338737.542     1596477.926      338941.535
#Sta/Elev= 30
       0  842.65    39.1  847.57    87.9  849.52   107.4  847.86   117.2     845
   146.5  833.64     166  822.53   195.3  802.53   273.4  744.08     293  731.24
   302.9  726.62   371.7  710.58   450.5  707.82     480   697.5   499.6  693.27
     539  690.55   548.8  690.57   558.7  692.24   565.2694.8997   578.4  700.19
   588.2  702.48     598  702.93   814.5  697.22   834.2  697.65   853.9  704.67
   921.9  736.26   950.9  747.26   970.3   750.9  1018.7  755.69  1086.4  756.98
#Mann= 3 , 0 , 0
       0      .1       0   499.6    .045       0   565.2      .1       0
Bank Sta=499.6,565.2
XS Rating Curve= 0 ,0
Exp/Cntr=0.3,0.1

Type RM Length L Ch R = 1 ,4684.2  ,600.1,592.3,584.3
XS GIS Cut Line= 4
     1595540.426      338438.063     1595898.499      339141.188
     1596045.957       339702.66     1596265.094      340022.914
#Sta/Elev= 30
       0  825.66    48.7  796.38   107.2  769.25   185.1  729.54     224   713.1
     263  706.73   399.4  705.99   467.6  702.63   487.1   699.1   506.6  691.48
   533.6   689.2   555.3  689.76     565  692.53   594.2  708.08     604  710.91
   740.3  725.57   828.4  745.76   887.4  747.94   907.1  746.74   936.6  741.35
   956.3  741.26  1064.6   763.3  1192.5  785.08  1251.5  792.31  1359.7  800.86
    1486  819.07  1544.2  831.26  1641.2  861.84  1709.1  879.93  1757.6  887.92
#Mann= 3 , 0 , 0
       0      .1       0   506.6    .045       0     565    .065       0
Bank Sta=506.6,565
XS Rating Curve= 0 ,0
Exp/Cntr=0.3,0.1

Type RM Length L Ch R = 1 ,4092    ,544.9,536.9,529.1
XS GIS Cut Line= 5
     1594952.319      338830.858     1595326.184       339183.93
     1595525.235      339520.962     1595514.698      339773.865
      1595542.77      340254.323
#Sta/Elev= 30
       0  866.73    38.8  858.83    87.3   850.8   106.7   845.7     262  787.09
   271.7   782.3   281.4  775.69   300.8  757.89     359  701.14   370.8692.7214
   378.4  689.94   388.1   689.2   417.2  689.58   426.9  691.24   446.3  699.09
     456  701.65   465.7  702.48   592.5  706.53   641.4  705.28   758.9  708.37
     798  710.42   837.2  715.86   866.5  718.22   973.8     741  1178.4  772.64
    1365  796.96  1522.2  825.52  1551.7  832.19  1600.8   845.6  1640.1  853.31
#Mann= 3 , 0 , 0
       0      .1       0   370.8    .045       0   426.9    .065       0
Bank Sta=370.8,426.9
XS Rating Curve= 0 ,0
Exp/Cntr=0.3,0.1

Type RM Length L Ch R = 1 ,3555    ,564.9,567.2,569
XS GIS Cut Line= 4
     1594315.898      339116.222     1594592.287      339403.722
     1595336.075      339723.486     1595437.128      339976.691
#Sta/Elev= 30
       0  787.34   155.6  775.76   369.6  766.34   398.8  766.15   428.1  763.49
   496.4  761.08   545.1  753.12   574.4  746.51   642.7  726.63   720.7  699.42
   730.5  697.33     789  690.39   818.2   689.2   837.8  689.31   852.7692.3069
     867  697.77   876.8  699.93     945  699.29   954.8  699.83   984.1  705.26
  1042.6  705.28  1130.4  708.45  1140.1  710.29  1159.6  717.52  1188.9  722.42
  1247.4  743.01  1286.3  759.65  1315.5  767.94  1393.4  784.09    1481  793.96
#Mann= 3 , 0 , 0
       0      .1       0     789    .045       0   852.7     .06       0
Bank Sta=789,852.7
XS Rating Curve= 0 ,0
Exp/Cntr=0.3,0.1

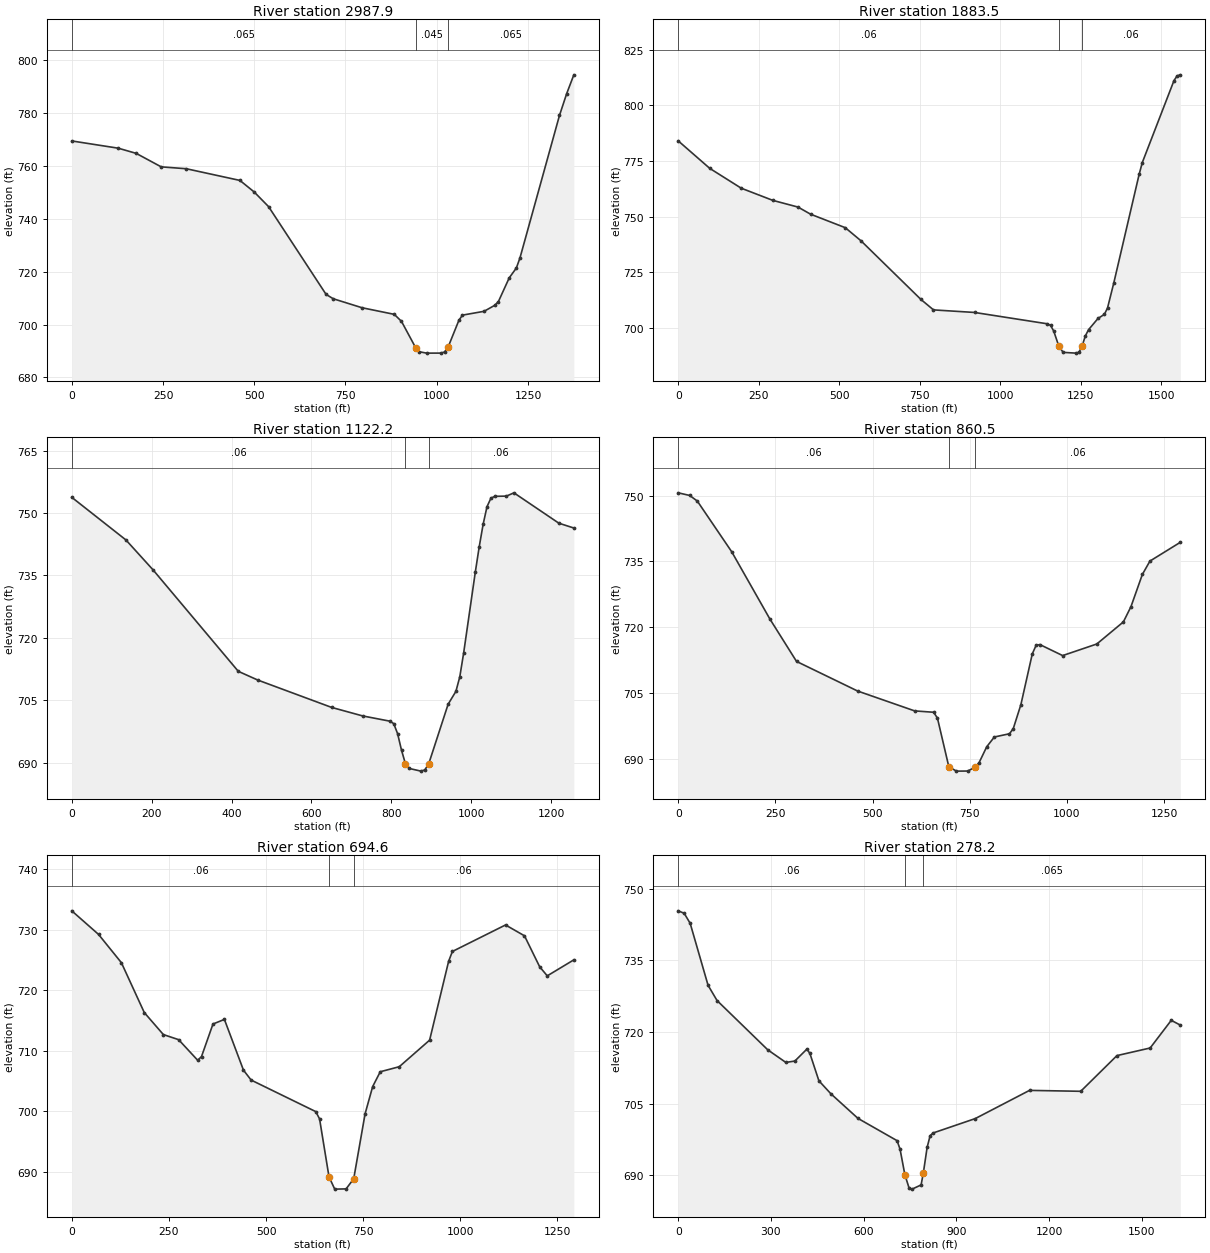
Type RM Length L Ch R = 1 ,2987.9  ,1095.1,1104.4,1113.3
XS GIS Cut Line= 3
     1594042.842      339424.277     1594309.509      339847.194
     1595079.532      340264.229
#Sta/Elev= 30
       0  769.31   127.4  766.57   176.5  764.62   245.1  759.52   313.7  758.82
   460.8   754.4     500  750.02   539.3   744.5   696.8  711.38   716.4  709.73
   795.2  706.34   883.7  703.84   903.4   701.2   942.7  691.13   952.6  689.71
   972.3   689.2  1011.6  689.21  1021.4  689.63  1031.3  691.52  1060.8  701.62
  1070.6  703.55  1129.7  704.99  1159.2  707.27    1169  708.66  1198.6  717.61
  1218.2  721.34  1228.1  725.16  1336.3  778.92    1356  787.15  1375.7  794.27
#Mann= 3 , 0 , 0
       0    .065       0   942.7    .045       0  1031.3    .065       0
Bank Sta=942.7,1031.3
XS Rating Curve= 0 ,0
Exp/Cntr=0.3,0.1

Type RM Length L Ch R = 1 ,1883.5  ,757.6,761.3,765
XS GIS Cut Line= 3
     1593353.259      339940.944     1593828.537      340647.333
     1594268.595      341201.729
#Sta/Elev= 30
       0  784.04    97.9  771.69   195.7  762.78   293.6  757.32   371.9  754.31
     411  751.11   518.7  745.05   567.6  739.15   753.5  712.84   792.7  708.12
   920.2  706.97  1146.3  701.87  1156.2  701.15    1166  698.64  1182.1691.7443
  1195.5  689.04  1234.8   688.7  1244.6  689.07  1254.5  692.05  1264.3  696.42
  1274.1   699.2  1303.6  704.28  1323.3   706.1  1333.1  708.94  1352.8  720.34
  1431.4  769.04  1441.2  774.32  1539.6  811.14  1549.4  813.26  1559.2  813.71
#Mann= 3 , 0 , 0
       0     .06       0  1182.1    .045       0  1254.5     .06       0
Bank Sta=1182.1,1254.5
XS Rating Curve= 0 ,0
Exp/Cntr=0.3,0.1

Type RM Length L Ch R = 1 ,1122.2  ,266.2,261.7,257
XS GIS Cut Line= 4
     1592971.242      340607.345     1593148.711      340861.331
     1593526.484       341541.79      1593692.27      341573.393
#Sta/Elev= 30
       0  753.79   135.6  743.54   203.3  736.37   416.9  711.96   465.5  709.87
   650.4  703.29   728.2  701.24   796.3  699.98     806  699.39   815.7  696.97
   825.5  692.99   835.2  689.78   844.9  688.61   874.1  687.97   883.8  688.26
   893.6  689.73   942.2  704.06   961.7  707.15   971.4  710.65   981.1  716.41
  1010.3  735.87    1020  741.89  1029.8   747.3  1039.5  751.54  1049.2  753.56
    1059  754.03  1088.1  754.08  1106.9  754.87  1219.4  747.57  1256.9  746.41
#Mann= 3 , 0 , 0
       0     .06       0   835.2    .045       0   893.6     .06       0
Bank Sta=835.2,893.6
XS Rating Curve= 0 ,0
Exp/Cntr=0.3,0.1

Type RM Length L Ch R = 1 ,860.5   ,167,165.9,164.8
XS GIS Cut Line= 3
     1592829.335      340841.369     1593046.349      341303.652
     1593553.294       341898.27
#Sta/Elev= 30
       0  750.64    29.5  750.04    49.1  748.76   137.5  737.22   235.7   721.9
   304.4  712.21   461.6  705.46   608.4  700.93   657.2  700.62     667   699.3
   696.3  688.23   715.8   687.2   745.1  687.22   764.6  688.12   774.4  689.16
   793.9  692.75   813.5  694.98   852.5  695.72   862.3  696.91   881.8  702.35
   911.2  713.94   920.9  715.86   930.7  716.05   989.3  713.54  1077.2  716.18
  1145.6  721.22  1165.1  724.69  1194.4  732.03  1213.9  735.08  1292.1  739.36
#Mann= 3 , 0 , 0
       0     .06       0   696.3    .045       0   764.6     .06       0
Bank Sta=696.3,764.6
XS Rating Curve= 0 ,0
Exp/Cntr=0.3,0.1

Type RM Length L Ch R = 1 ,694.6   ,399.4,416.4,433.5
XS GIS Cut Line= 3
     1592694.447      340918.032     1592911.461      341380.315
     1593418.405      341974.933
#Sta/Elev= 30
       0  733.08    68.8   729.2   127.7  724.53   186.6  716.31   235.7  712.68
     275  711.84   324.1  708.44   333.9  709.06   363.4  714.42   392.8  715.18
   441.9  706.81   461.6  705.18   627.9  699.98   637.7  698.78     662689.2321
   676.7   687.2     706  687.24   725.6  688.91   754.9  699.63   774.4  704.11
   793.9  706.55   842.8  707.38   920.9  711.76   969.8  724.75   979.5  726.38
  1116.3  730.75  1165.1  728.96  1204.2  723.85  1223.7  722.36  1292.1     725
#Mann= 3 , 0 , 0
       0     .06       0     662    .045       0   725.6     .06       0
Bank Sta=662,725.6
XS Rating Curve= 0 ,0
Exp/Cntr=0.3,0.1

Type RM Length L Ch R = 1 ,278.2   ,282.6,278.2,273.8
XS GIS Cut Line= 5
       1592612.4      340785.233     1592614.212      341075.131
     1592614.215       341688.08      1592797.21       341999.18
     1593099.791      342196.673
#Sta/Elev= 30
       0  745.33    19.3  744.81    38.6  742.72    96.6  729.74   125.6  726.56
   289.9  716.24   348.3  713.61   377.5   713.9   416.4   716.4   426.1   715.5
   455.3  709.77   494.2  707.04   581.8   701.9   708.3  697.24     718  695.45
   733.5690.1388   747.2  687.32   756.9   687.1   786.1  687.98   793.5690.5509
   805.6  695.83   815.3  698.28     825  698.85   961.4  701.86    1137  707.76
  1302.8  707.57    1420  715.04  1527.5  716.63  1595.8  722.42  1625.1  721.42
#Mann= 3 , 0 , 0
       0     .06       0   733.5    .045       0   793.5    .065       0
Bank Sta=733.5,793.5
XS Rating Curve= 0 ,0
Exp/Cntr=0.3,0.1

Chan Stop Cuts=-1
Use User Specified Reach Order=0
Composite Channel Slope=5